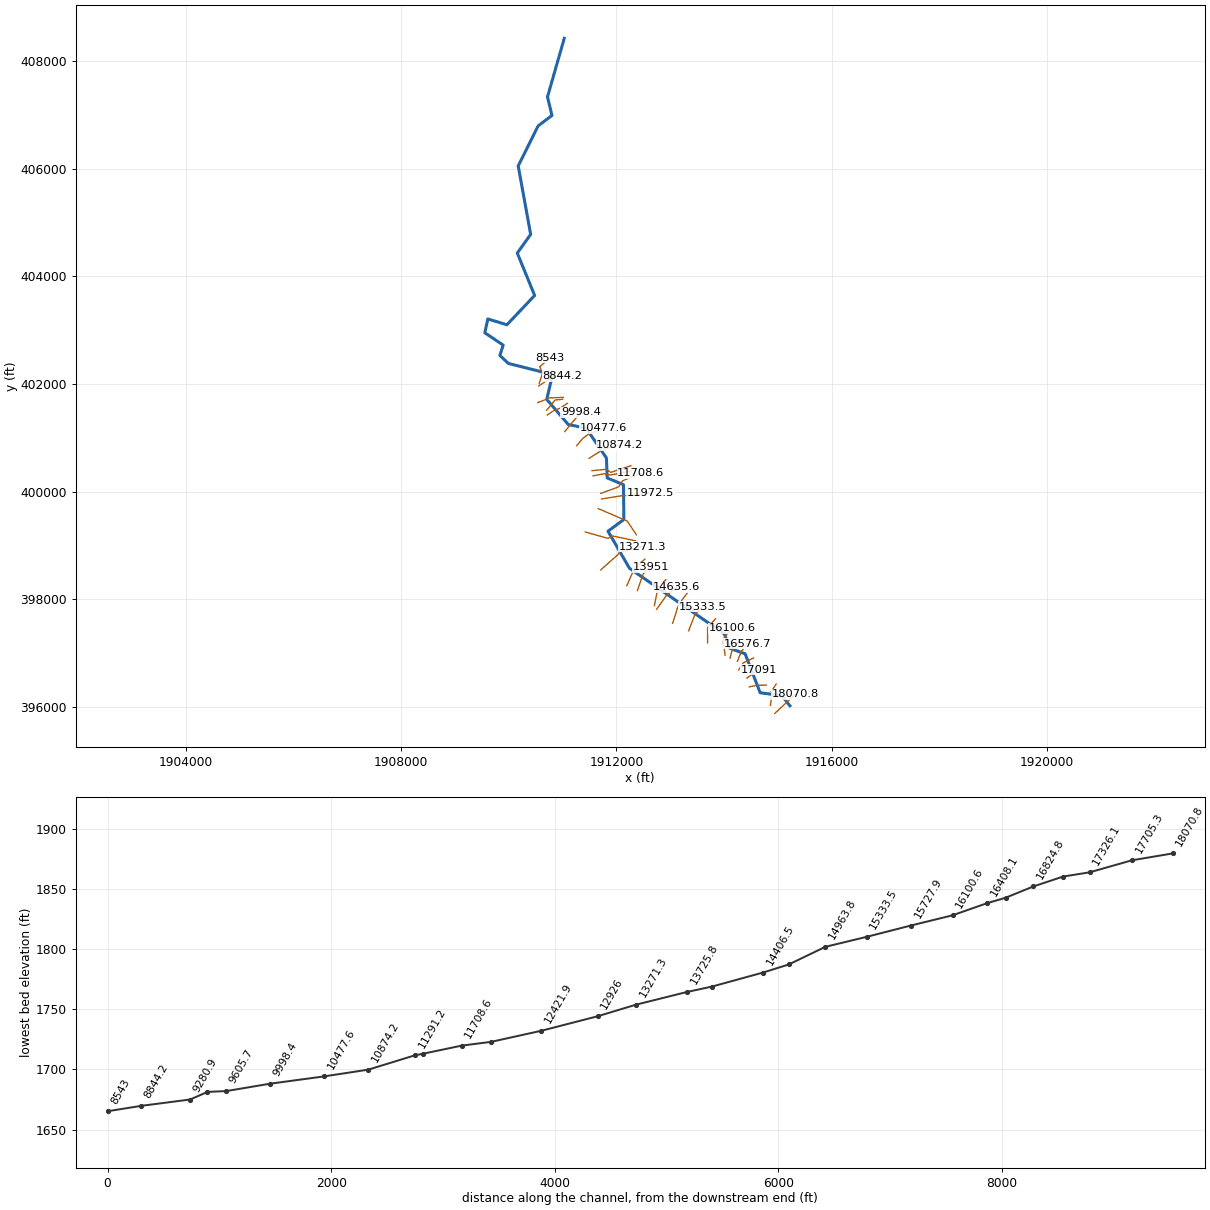
--- SOVERNRN.prj (project) ---

Proj Title=SOVERNRN
Current Plan=p01
Default Exp/Contr=0,0
English Units
Geom File=g01
Flow File=f01
Plan File=p01
BEGIN DESCRIPTION:
END DESCRIPTION:
DSS Export Rating Curves= 0
DSS Export Rating Curve Sorted= 0
DSS Export Volume Flow Curves= 0
DXF OffsetX= 0
DXF OffsetY= 0
DXF ScaleX= 0
DXF ScaleY= 0

--- SOVERNRN.p01 (plan) ---

Plan Title=Floodplain
Program Version=4.00
Geom File=g01
Flow File=f01
K Sum by GR=0
Std Step Tol=0.01
Critical Tol=0.01
Num of Std Step Trials=20
Max Error Tol=0.3
Flow Tol Ratio=0.001
Split Flow NTrial=30
Split Flow Tol=0.02
Split Flow Ratio=0.02
Log Output Level=0
Friction Slope Method=1
Unsteady Friction Slope Method=2
Unsteady Bridges Friction Slope Method=1
Global Log Level=0
CheckData=False
Run HTab=0
Run UNet=0
Run PostProcess=0
UNET Theta=0
UNET Theta Warmup=0
UNET ZTol=0
UNET ZSATol=0
UNET MxIter=0
UNET MaxInSteps=0
UNET DtIC=0
UNET DtMin=0
UNET MaxCRTS=0
UNET WFStab=0
UNET SFStab=0
UNET WFX=0
UNET SFX=0
UNET DSS MLevel=0
UNET DZMax Abort=0
UNET Convert EG Bridges=0
UNET Use Existing IB Tables=0
UNET Froude Limit=0
UNET Froude Power=0
Write IC File=0
Echo Input=False
Echo Output=False
Write Detailed=0

--- SOVERNRN.f01 (steady flow) ---

Flow Title=NFF Regression Equation
Program Version=4.00
Number of Profiles=1
Profile Names=P100yr
River Rch & RM=SOVERNRN,Main      ,18070.8
519.0760
River Rch & RM=SOVERNRN,Main      ,13951
578.2698
River Rch & RM=SOVERNRN,Main      ,11972.5
644.5480
River Rch & RM=SOVERNRN,Main      ,11708.6
686.1772
River Rch & RM=SOVERNRN,Main      ,8289.4
727.7333
River Rch & RM=SOVERNRN,Main      ,7873.4
897.4097
River Rch & RM=SOVERNRN,Main      ,5453.5
933.2023
River Rch & RM=SOVERNRN,Main      ,4662.9
1056.867
River Rch & RM=SOVERNRN,Main      ,281.2
1140.819
Boundary for River Rch & Prof#=SOVERNRN,Main      ,1
Up Type=0
Dn Type=3
Dn Slope=0.128363

--- SOVERNRN.g01 (geometry) ---

Geom Title=USGS 10m DEM
Program Version=4.10

River Reach=SOVERNRN        ,Main
Reach XY= 30
     1915225.798      396023.719     1915072.369      396211.653
     1914672.412       396265.69     1914392.464      396988.889
     1914108.176      397090.885     1914006.158      397358.014
     1912242.942       398577.43     1911843.636      399265.364
     1912138.318      399483.354      1912131.18      400130.165
     1911828.445       400255.49     1911814.255      400626.554
      1911435.65      401181.597     1911105.789      401246.701
     1910705.026      401714.397      1910812.82      402176.063
     1909992.485      402382.021     1909833.003      402530.881
     1909894.852      402722.938     1909553.202      402951.906
     1909609.587      403208.661     1909964.296      403100.542
     1910479.704      403644.705     1910157.438      404432.465
     1910405.919      404779.145     1910173.714      406050.846
     1910544.808      406795.204      1910801.97      406988.889
     1910718.419       407331.77     1911030.486       408421.24

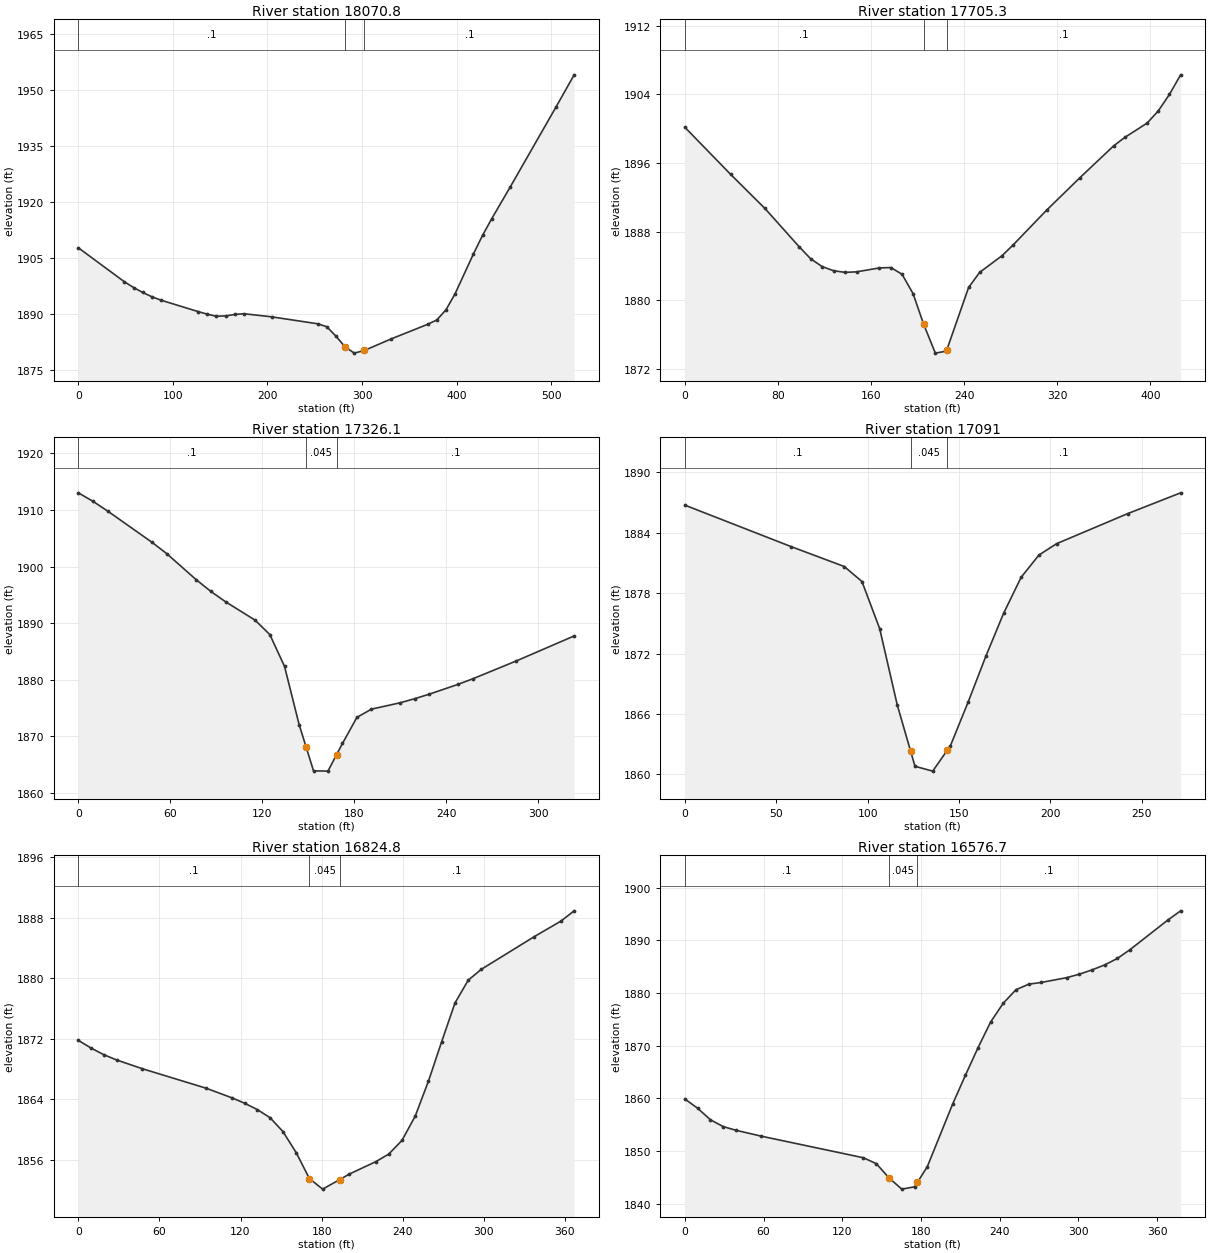
Type RM Length L Ch R = 1 ,18070.8 ,340,365.6,390.4
XS GIS Cut Line= 3
     1914945.785      395882.118     1915123.736      396048.133
     1915330.984       396238.02
#Sta/Elev= 30
       0 1907.73    48.7 1898.64    58.4  1897.1    68.1 1895.77    77.9 1894.62
    87.6  1893.7   126.6 1890.67   136.3 1889.97     146 1889.42   155.8  1889.5
   165.5  1889.9   175.2 1890.09   204.4 1889.26   253.1  1887.4   262.8 1886.61
   272.4  1884.1   282.1 1881.23   291.8 1879.55   302.5 1880.26   330.6 1883.32
   369.4 1887.25   379.1 1888.42   388.8 1891.12   398.4  1895.4   417.8 1906.05
   427.5 1911.04   437.2  1915.5   456.6 1923.91   505.1 1945.34   524.4 1953.99
#Mann= 3 , 0 , 0
       0      .1       0   282.1    .045       0   302.5      .1       0
Bank Sta=282.1,302.5
XS Rating Curve= 0 ,0
Exp/Cntr=0.3,0.1

Type RM Length L Ch R = 1 ,17705.3 ,421.6,379.1,336
XS GIS Cut Line= 4
     1914862.234      396030.772     1914891.531      396205.468
     1914877.425      396290.104     1914969.656      396424.652
#Sta/Elev= 29
       0 1900.17    39.4 1894.67    68.9 1890.69    98.4 1886.21   108.2 1884.82
   118.1 1883.91   127.9 1883.43   137.8 1883.24   147.6  1883.3   167.3 1883.76
   177.1  1883.8   186.7 1883.02   196.2 1880.75   205.2 1877.21   215.3 1873.82
   224.8 1874.05   225.2 1874.21   243.9 1881.48   253.4 1883.24   272.5 1885.17
   282.1 1886.43   310.9 1890.49   339.7  1894.3   368.5 1897.99   378.1 1898.98
   397.3 1900.65   406.9 1902.07   416.5    1904   426.1 1906.28
#Mann= 3 , 0 , 0
       0      .1       0   205.2    .045       0   225.2      .1       0
Bank Sta=205.2,225.2
XS Rating Curve= 0 ,0
Exp/Cntr=0.3,0.1

Type RM Length L Ch R = 1 ,17326.1 ,220.6,235.2,249.5
XS GIS Cut Line= 3
     1914469.439      396373.654     1914600.733      396402.951
     1914789.535      396408.376
#Sta/Elev= 26
       0 1913.03     9.6 1911.52    19.2 1909.79      48 1904.29    57.6 1902.29
    76.9 1897.66    86.5 1895.58    96.1 1893.75   115.3 1890.51   124.9 1887.96
   134.5 1882.33     144 1872.05   148.5 1868.13   153.4 1863.86   162.8 1863.81
   168.5 1866.75   172.3 1868.71   181.7 1873.32   191.2 1874.77   210.1 1875.91
   219.5 1876.63     229 1877.43   247.8 1879.17   257.3 1880.14   285.6 1883.29
   323.4 1887.72
#Mann= 3 , 0 , 0
       0      .1       0   148.5    .045       0   168.5      .1       0
Bank Sta=148.5,168.5
XS Rating Curve= 0 ,0
Exp/Cntr=0.3,0.1

Type RM Length L Ch R = 1 ,17091   ,270.2,266.1,262.1
XS GIS Cut Line= 2
     1914427.122      396539.127     1914649.561      396694.292
#Sta/Elev= 19
       0 1886.76    58.1 1882.64    87.2 1880.66    96.9 1879.17   106.6 1874.48
   116.2 1866.91   123.5 1862.32   125.9 1860.81   135.6 1860.33   143.5 1862.39
   145.3 1862.86     155  1867.2   164.7 1871.76   174.4 1876.02     184  1879.6
   193.7  1881.8   203.4 1882.93   242.2 1885.91   271.2 1887.98
#Mann= 3 , 0 , 0
       0      .1       0   123.5    .045       0   143.5      .1       0
Bank Sta=123.5,143.5
XS Rating Curve= 0 ,0
Exp/Cntr=0.3,0.1

Type RM Length L Ch R = 1 ,16824.8 ,228.3,248.1,266.9
XS GIS Cut Line= 3
     1914273.128      396690.603     1914355.594      396817.556
     1914549.821      396910.872
#Sta/Elev= 28
       0  1871.8     9.5 1870.77    18.9  1869.9    28.4  1869.2    47.3 1868.05
    94.6 1865.47   113.5 1864.21     123 1863.49   132.5 1862.64   141.9 1861.57
   151.4 1859.74   161.2 1856.96     171 1853.52   180.8 1852.13   193.5  1853.4
   200.4 1854.11     220 1855.75   229.7 1856.76   239.5 1858.57   249.3 1861.79
   259.1 1866.41   268.9 1871.64   278.7 1876.73   288.5 1879.75   298.3  1881.2
   337.5 1885.52   357.1 1887.56   366.9 1888.92
#Mann= 3 , 0 , 0
       0      .1       0     171    .045       0   193.5      .1       0
Bank Sta=171,193.5
XS Rating Curve= 0 ,0
Exp/Cntr=0.3,0.1

Type RM Length L Ch R = 1 ,16576.7 ,165.5,168.6,171.5
XS GIS Cut Line= 3
     1914248.953      396848.589     1914320.568      397029.579
     1914429.943      397176.714
#Sta/Elev= 29
       0 1859.87     9.7 1858.13    19.5 1855.93    29.2 1854.63    38.9 1853.93
    58.4  1852.8   136.2  1848.7     146 1847.58   155.7 1844.88   165.4 1842.74
   175.2 1843.18   177.4 1844.05   184.9 1847.02   204.3 1858.97   213.9 1864.36
   223.6 1869.65   233.2 1874.52   242.9 1878.11   252.5 1880.64   262.2 1881.69
   271.8 1882.02   291.1 1882.93   300.8 1883.59   310.4  1884.4   320.1 1885.35
   329.7 1886.57   339.4 1888.25   368.3 1893.89     378 1895.63
#Mann= 3 , 0 , 0
       0      .1       0   155.7    .045       0   177.4      .1       0
Bank Sta=155.7,177.4
XS Rating Curve= 0 ,0
Exp/Cntr=0.3,0.1

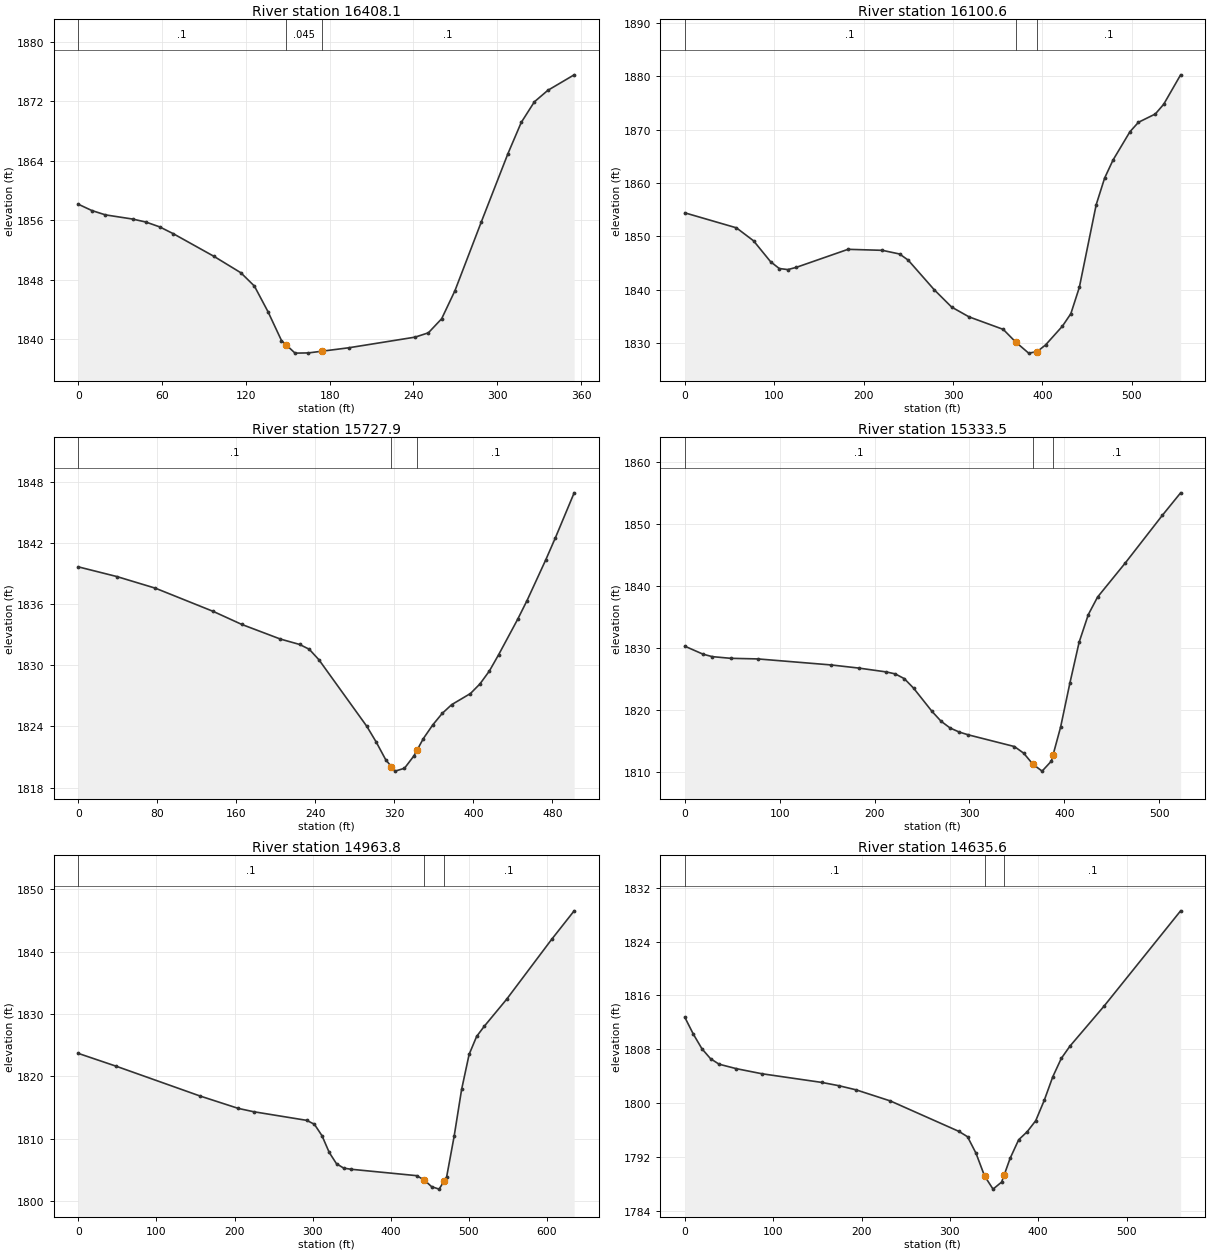
Type RM Length L Ch R = 1 ,16408.1 ,318.1,307.5,296.6
XS GIS Cut Line= 3
     1914111.284      396907.147     1914159.027      397085.098
     1914269.704      397215.306
#Sta/Elev= 27
       0 1858.15     9.7  1857.3    19.4 1856.72    38.8 1856.16    48.5 1855.75
    58.2 1855.11    67.9  1854.2      97 1851.16   116.4 1848.94   126.1 1847.15
   135.8 1843.72   145.5 1839.83   148.8 1839.26   155.2 1838.14   164.8 1838.17
   174.6  1838.4   193.7 1838.86   241.2 1840.29   250.7 1840.87   260.2 1842.76
   269.7 1846.52   288.7 1855.82   307.7 1864.96   317.2 1869.14   326.6 1871.91
   336.2 1873.45   355.1 1875.54
#Mann= 3 , 0 , 0
       0      .1       0   148.8    .045       0   174.6      .1       0
Bank Sta=148.8,174.6
XS Rating Curve= 0 ,0
Exp/Cntr=0.3,0.1

Type RM Length L Ch R = 1 ,16100.6 ,381.4,372.7,371
XS GIS Cut Line= 4
     1914021.089      396963.823     1913985.932      397211.219
     1914008.068      397295.855     1914147.391      397462.521
#Sta/Elev= 30
       0  1854.4    57.7 1851.59    76.9 1849.16    96.1 1845.21   105.7 1843.96
   115.3 1843.76   124.9 1844.19   182.6 1847.56     221 1847.37   240.3 1846.68
   249.9 1845.53     279 1839.98   298.5 1836.73   317.9  1834.9   356.2 1832.55
     370  1830.2   384.6  1828.1     394 1828.37   403.5 1829.63   422.4 1833.16
   431.8 1835.49   441.3 1840.42   460.2 1855.95   469.6 1860.92     479  1864.3
   497.9  1869.6   507.4 1871.37   526.3 1872.93   535.7 1874.76   554.6 1880.27
#Mann= 3 , 0 , 0
       0      .1       0     370    .045       0     394      .1       0
Bank Sta=370,394
XS Rating Curve= 0 ,0
Exp/Cntr=0.3,0.1

Type RM Length L Ch R = 1 ,15727.9 ,384.2,394.5,394.8
XS GIS Cut Line= 3
     1913694.266      397194.292     1913695.568      397476.844
     1913842.703      397639.605
#Sta/Elev= 30
       0 1839.64      39 1838.69      78 1837.55   136.4 1835.28   165.6 1833.99
   204.6 1832.56   224.1 1832.03   233.8 1831.56   243.6 1830.53   292.1    1824
   301.6 1822.46   311.2 1820.73  316.911820.057   320.7 1819.61   330.2 1819.89
   339.8 1821.11   342.9 1821.66   349.3  1822.8   358.9 1824.15   368.4 1825.27
     378 1826.13     397 1827.22   406.6 1828.16   416.1 1829.42   425.6 1831.04
   444.7 1834.48   454.3 1836.34   473.3 1840.34   482.9 1842.47     502  1846.9
#Mann= 3 , 0 , 0
       0      .1       0  316.91    .045       0   342.9      .1       0
Bank Sta=316.91,342.9
XS Rating Curve= 0 ,0
Exp/Cntr=0.3,0.1

Type RM Length L Ch R = 1 ,15333.5 ,366.2,369.6,372.7
XS GIS Cut Line= 3
     1913342.703      397416.948     1913457.286      397713.823
     1913599.214      397860.959
#Sta/Elev= 30
       0 1830.34    19.3 1829.05    28.9 1828.66    48.2 1828.39    77.1 1828.29
   154.3 1827.32   183.2 1826.82   212.2  1826.2   221.8 1825.88   231.4 1825.11
   241.1 1823.59   260.4 1819.87     270 1818.27   279.6 1817.17   289.3 1816.51
   298.9 1816.06   347.4 1814.18   357.2 1813.11   366.9 1811.33   376.6 1810.22
   386.4 1811.84   388.2 1812.86   396.1 1817.31   405.8 1824.34   415.6 1830.97
   425.3 1835.43     435 1838.24   464.2 1843.73   503.2 1851.39   522.6 1855.04
#Mann= 3 , 0 , 0
       0      .1       0   366.9    .045       0   388.2      .1       0
Bank Sta=366.9,388.2
XS Rating Curve= 0 ,0
Exp/Cntr=0.3,0.1

Type RM Length L Ch R = 1 ,14963.8 ,334.8,328.3,321.3
XS GIS Cut Line= 4
     1913045.398      397555.671     1913139.426      397853.198
     1913187.755       397942.99     1913317.964      398121.376
#Sta/Elev= 26
       0  1823.7    48.8 1821.63     156 1816.86   204.8 1814.88   224.3 1814.35
   292.5 1812.96   302.3 1812.33     312  1810.5   321.3 1807.81   330.6    1806
   339.8  1805.3   349.1 1805.12   433.2 1804.09   442.8 1803.41   452.4 1802.32
     462 1801.93   468.2 1803.19   471.6 1803.88   481.2 1810.39   490.8 1817.93
   500.4 1823.54     510 1826.42   519.6 1828.02   548.4 1832.38     606 1841.98
   634.9 1846.57
#Mann= 3 , 0 , 0
       0      .1       0   442.8    .045       0   468.2      .1       0
Bank Sta=442.8,468.2
XS Rating Curve= 0 ,0
Exp/Cntr=0.3,0.1

Type RM Length L Ch R = 1 ,14635.6 ,210.9,229.1,247.2
XS GIS Cut Line= 3
     1912747.651      397815.386     1912926.036      398069.292
     1913121.349      398226.844
#Sta/Elev= 28
       0 1812.76     9.7 1810.24    19.4 1808.08    29.1 1806.61    38.8 1805.79
    58.2 1805.13    87.3 1804.37   155.2 1803.08   174.6 1802.59   193.9 1801.98
   232.7 1800.33   310.3 1795.81     320 1795.02   329.6 1792.57   339.3 1789.19
   348.9 1787.24   358.6 1788.29   361.5 1789.35   368.2 1791.81   377.9 1794.57
   387.5 1795.76   397.2  1797.4   406.8 1800.41   416.5 1803.92   426.1 1806.64
   435.8 1808.45   474.4 1814.39   561.2 1828.56
#Mann= 3 , 0 , 0
       0      .1       0   339.3    .045       0   361.5      .1       0
Bank Sta=339.3,361.5
XS Rating Curve= 0 ,0
Exp/Cntr=0.3,0.1

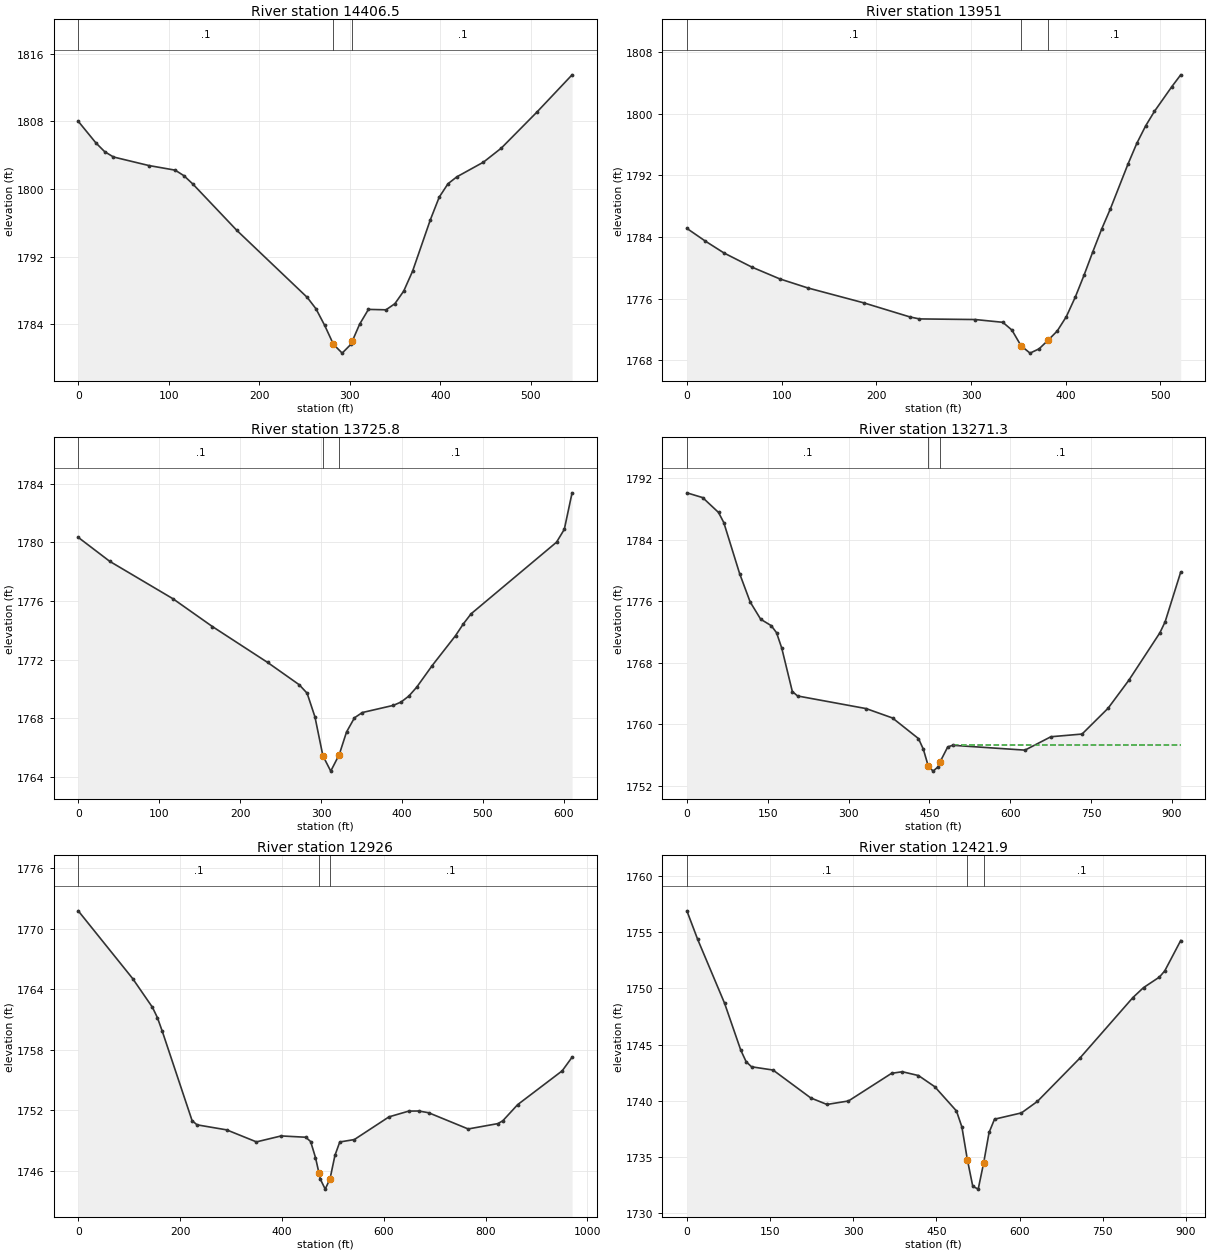
Type RM Length L Ch R = 1 ,14406.5 ,467.8,455.5,442.4
XS GIS Cut Line= 4
     1912706.505      397885.264     1912752.078      398114.431
     1912769.005      398209.483     1912918.224      398364.865
#Sta/Elev= 30
       0 1808.02    19.5 1805.46    29.2 1804.42    38.9 1803.79    77.9 1802.78
   107.1 1802.23   116.8 1801.57   126.6 1800.59   175.2  1795.1     253 1787.16
   262.6 1785.82   272.3 1783.84   281.9 1781.61   291.6 1780.56   301.2  1781.6
     303 1782.04   310.9 1783.99   320.6 1785.74     340 1785.69   349.8 1786.41
   359.6 1787.91   369.4 1790.27     389 1796.35   398.8 1799.03   408.5 1800.62
   418.3 1801.44   447.7 1803.18   467.3 1804.83   506.5 1809.08   545.6 1813.52
#Mann= 3 , 0 , 0
       0      .1       0   281.9    .045       0     303      .1       0
Bank Sta=281.9,303
XS Rating Curve= 0 ,0
Exp/Cntr=0.3,0.1

Type RM Length L Ch R = 1 ,13951   ,217.8,225.2,232
XS GIS Cut Line= 4
     1912389.578      398163.042     1912496.349      398469.032
     1912551.036      398535.438     1912644.786      398595.334
#Sta/Elev= 29
       0 1785.13    19.6 1783.47    39.3 1781.93    68.7  1780.1    98.2 1778.57
   127.7  1777.4   186.6 1775.47   235.7 1773.63   245.5 1773.38   304.4  1773.3
   333.6 1772.94   343.2 1771.93   352.8  1769.9   362.3 1768.94   371.9  1769.5
   381.4 1770.62     391 1771.81   400.6 1773.67   410.1 1776.22   419.4 1779.08
   428.6  1782.1   437.9 1785.03   447.2 1787.69   465.7 1793.47     475 1796.16
   484.3 1798.42   493.6 1800.31   512.1 1803.54   521.4 1805.06
#Mann= 3 , 0 , 0
       0      .1       0   352.8    .045       0   381.4      .1       0
Bank Sta=352.8,381.4
XS Rating Curve= 0 ,0
Exp/Cntr=0.3,0.1

Type RM Length L Ch R = 1 ,13725.8 ,461.6,454.5,447.3
XS GIS Cut Line= 3
     1912192.964      398252.886     1912333.589      398574.501
     1912527.599      398746.376
#Sta/Elev= 25
       0 1780.35      39 1778.71     117 1776.16   165.8 1774.26     234 1771.81
     273 1770.29   282.8 1769.71   292.5 1768.09   302.3 1765.44     312 1764.39
   322.5 1765.52   331.5 1767.06   341.3 1768.03     351 1768.39   389.4 1768.88
     399 1769.11   408.6 1769.52   418.2 1770.12   437.4  1771.6   466.2 1773.64
   475.8 1774.44   485.4 1775.13     591 1780.02   600.6  1780.9   610.2 1783.39
#Mann= 3 , 0 , 0
       0      .1       0   302.3    .045       0   322.5      .1       0
Bank Sta=302.3,322.5
XS Rating Curve= 0 ,0
Exp/Cntr=0.3,0.1

Type RM Length L Ch R = 1 ,13271.3 ,356,345.2,334.3
XS GIS Cut Line= 4
     1911706.857      398545.254     1912021.093      398824.768
     1912073.176      398887.268     1912476.818      398979.448
#Sta/Elev= 30
       0 1790.07    29.3 1789.45    58.7 1787.52    68.5  1786.2    97.8 1779.58
   117.4 1775.88   136.9 1773.64   156.5  1772.8   166.3 1771.89     176 1769.88
   195.6 1764.24   205.4 1763.66   332.5 1762.02   381.4  1760.8   429.6 1758.12
   438.6 1756.74   447.7 1754.56   456.7 1753.89   465.8 1754.44   469.6 1755.09
   483.8 1757.03   492.9 1757.25   627.1 1756.62   675.2 1758.36     733 1758.71
   781.2 1762.06   819.7  1765.7   877.4 1771.88   887.1 1773.31     916 1779.77
#Mann= 3 , 0 , 0
       0      .1       0   447.7    .045       0   469.6      .1       0
#XS Ineff= 2 , 0
                          493.07         1757.29
Permanent Ineff=
       F       F
Bank Sta=447.7,469.6
XS Rating Curve= 0 ,0
Exp/Cntr=0.3,0.1

Type RM Length L Ch R = 1 ,12926   ,525.2,504.1,482.5
XS GIS Cut Line= 4
     1911420.398      399251.852     1911841.401      399133.094
     1911936.887      399176.497      1912355.29      399087.955
#Sta/Elev= 30
       0 1771.78   106.9 1765.07   145.8 1762.22   155.5  1761.2   165.2 1759.83
   223.6    1751   233.3 1750.58   291.6 1750.08     350 1748.89   398.6 1749.48
     447 1749.35   456.5 1748.92     466 1747.34     473 1745.77   475.6 1745.19
   485.1 1744.21   494.6 1745.24   504.2 1747.55   513.7 1748.88   542.3 1749.12
   610.4 1751.37   649.2 1751.94   668.7 1751.95   688.1 1751.78   765.9 1750.17
   824.2  1750.7   833.9 1750.98   863.1 1752.58   950.6 1755.93     970 1757.28
#Mann= 3 , 0 , 0
       0      .1       0     473    .045       0   494.6      .1       0
Bank Sta=473,494.6
XS Rating Curve= 0 ,0
Exp/Cntr=0.3,0.1

Type RM Length L Ch R = 1 ,12421.9 ,439.1,449.4,459.2
XS GIS Cut Line= 4
      1911663.28      399685.879     1912064.496      399512.268
     1912199.912      399454.977     1912370.915      399200.803
#Sta/Elev= 30
       0 1756.89    19.4 1754.36      68 1748.67    97.2  1744.5   106.9 1743.47
   116.6 1743.02   155.4 1742.73   223.4 1740.25   252.6 1739.67   291.4 1739.98
   369.2 1742.44   388.6 1742.58   417.7 1742.24     447 1741.25   486.2 1739.09
     496 1737.66   505.8 1734.77   515.6 1732.39   525.4 1732.14   535.2 1734.47
     545 1737.18   554.8 1738.36   603.4 1738.92   632.1 1739.94   708.7 1743.79
   804.4 1749.18   823.5 1750.06   852.2    1751   861.8 1751.55   890.6 1754.25
#Mann= 3 , 0 , 0
       0      .1       0   505.8    .045       0   535.2      .1       0
Bank Sta=505.8,535.2
XS Rating Curve= 0 ,0
Exp/Cntr=0.3,0.1

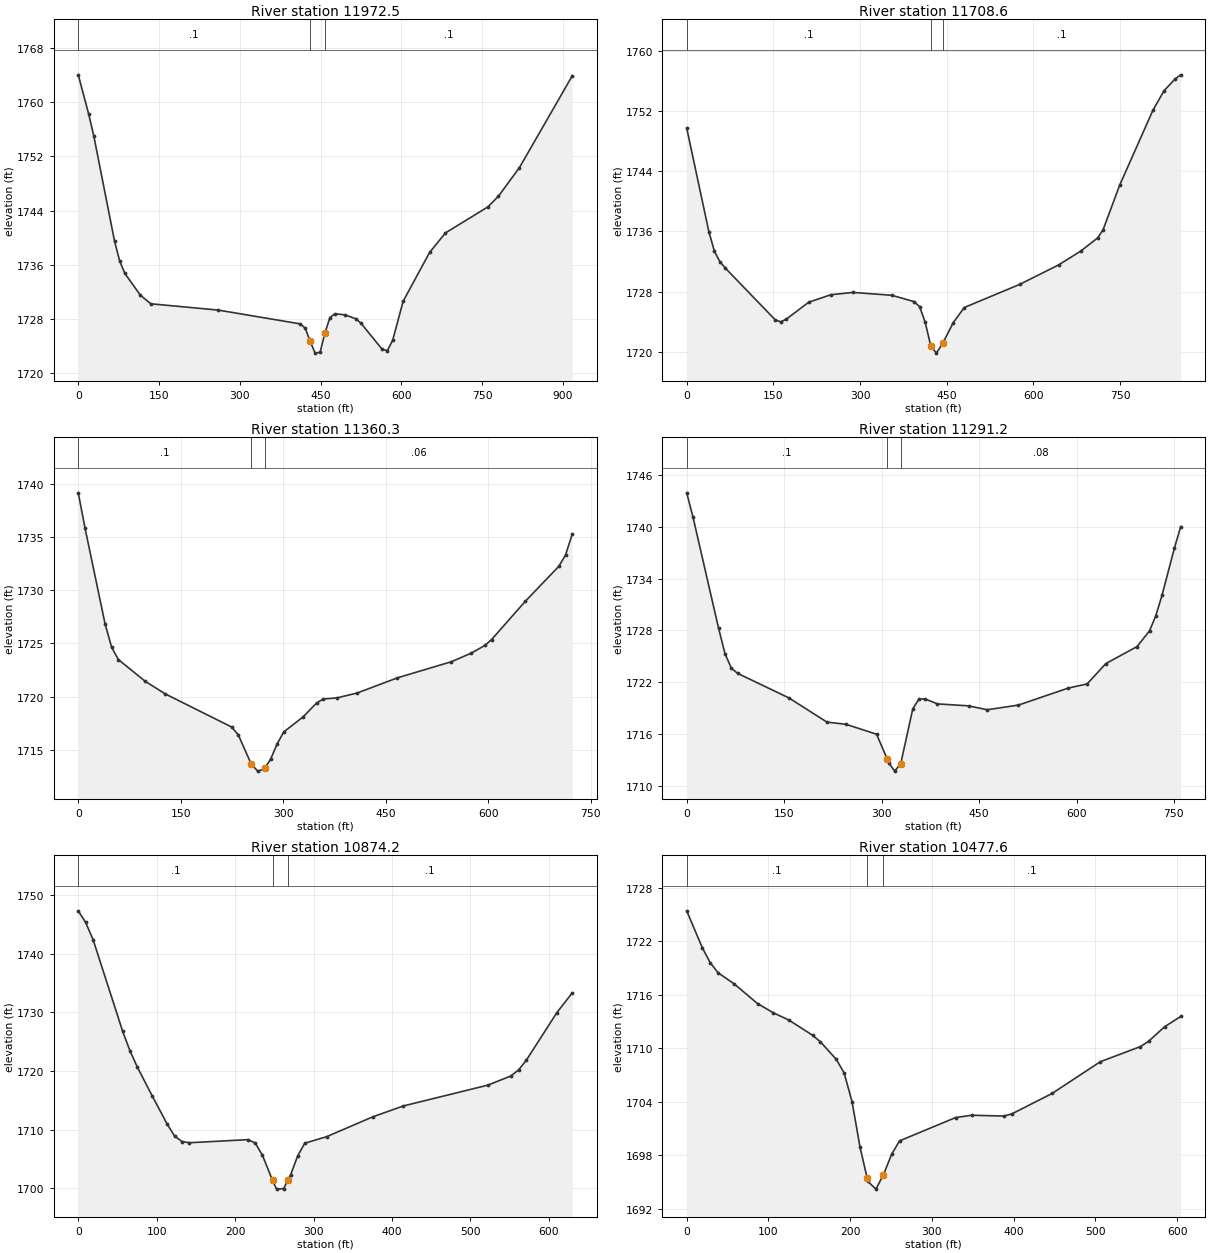
Type RM Length L Ch R = 1 ,11972.5 ,239.3,264,289.1
XS GIS Cut Line= 4
     1911723.345      399864.865     1912103.554      399925.629
     1912204.248      399925.629     1912633.068      399975.976
#Sta/Elev= 30
       0 1764.05    19.2 1758.31    28.9 1755.01    67.4 1739.49      77 1736.52
    86.6  1734.7   115.5 1731.48   134.8 1730.22   259.9 1729.29   412.5 1727.25
   421.6 1726.61   430.8 1724.65     440 1722.93   449.1 1723.05   458.3 1725.94
   467.4 1728.18   476.6 1728.74   495.5 1728.59   515.2 1728.01     525 1727.36
   564.2 1723.52     574 1723.29   583.9 1724.81   603.5 1730.61   652.6 1737.81
     682 1740.69   760.5 1744.52   780.1 1746.08   819.4 1750.34   917.5  1763.9
#Mann= 3 , 0 , 0
       0      .1       0   430.8    .045       0   458.3      .1       0
#XS Ineff= 2 , 0
                          478.18         1728.61
Permanent Ineff=
       F       F
Bank Sta=430.8,458.3
XS Rating Curve= 0 ,0
Exp/Cntr=0.3,0.1

Type RM Length L Ch R = 1 ,11708.6 ,377.6,348.3,318.5
XS GIS Cut Line= 4
     1911708.241      399968.337     1912041.575      400089.865
     1912116.227      400202.712     1912452.512      400344.032
#Sta/Elev= 30
       0 1749.78    38.4 1735.96      48 1733.34    57.5 1731.97    67.1  1731.1
   153.4 1724.21     163 1723.96   172.6 1724.33     211 1726.57   249.3 1727.57
   287.7 1727.88   354.8  1727.5   393.4 1726.66   403.1 1725.98   412.8 1723.88
   422.4 1720.73   432.1 1719.79   443.5 1721.16   461.1 1723.84   480.4 1725.87
   576.5 1728.96   643.7 1731.55   682.1  1733.4   710.9 1735.13   720.5 1736.22
   749.3 1742.18   806.9 1752.17   826.1 1754.77   845.3 1756.34   854.9 1756.88
#Mann= 3 , 0 , 0
       0      .1       0   422.4    .045       0   443.5      .1       0
Bank Sta=422.4,443.5
XS Rating Curve= 0 ,0
Exp/Cntr=0.3,0.1

Type RM Length L Ch R = 1 ,11360.3 ,77.9,69,59.8
XS GIS Cut Line= 4
       1911567.1      400293.518     1911768.923      400332.581
     1911890.451      400308.709     1912276.735      400384.664
#Sta/Elev= 30
       0 1739.17     9.8 1735.89    39.2 1726.86    48.9 1724.63    58.7 1723.48
    97.9 1721.44   127.3 1720.25   224.6 1717.13   234.2  1716.4   253.2 1713.65
   262.7 1712.98   272.3 1713.17   273.7 1713.31   281.8 1714.14   291.3 1715.56
   300.8 1716.67   329.4  1718.1   349.1 1719.41   358.9 1719.77   378.6 1719.87
   408.2 1720.33   467.2 1721.76   545.9 1723.27   575.5 1724.09   595.2 1724.81
     605 1725.36   654.2 1728.95   703.4 1732.25   713.3 1733.32   723.1 1735.29
#Mann= 3 , 0 , 0
       0      .1       0   253.2    .045       0   273.7     .06       0
Bank Sta=253.2,273.7
XS Rating Curve= 0 ,0
Exp/Cntr=0.3,0.1

Type RM Length L Ch R = 1 ,11291.2 ,388.7,417,445.3
XS GIS Cut Line= 4
     1911546.093      400390.306     1911799.999      400415.046
     1911896.353      400359.056      1912270.22      400482.921
#Sta/Elev= 30
       0  1743.9     9.8 1741.06    49.1 1728.24    58.9 1725.33    68.7 1723.64
    78.5 1723.04     157 1720.22   215.9 1717.41   245.3 1717.16   292.3 1716.01
   308.4 1713.19   310.8 1712.72   320.1 1711.75   329.4  1712.6     348 1718.95
   357.3 1720.05   366.6  1720.1   385.8 1719.52   433.8 1719.29   462.6 1718.84
   510.6 1719.38   587.5 1721.35   616.3 1721.82   645.1 1724.17   693.2 1726.14
   712.4 1727.96     722 1729.69   731.6 1732.06   750.8 1737.54   760.4    1740
#Mann= 3 , 0 , 0
       0      .1       0   308.4    .045       0   329.4     .08       0
Bank Sta=308.4,329.4
XS Rating Curve= 0 ,0
Exp/Cntr=0.3,0.1

Type RM Length L Ch R = 1 ,10874.2 ,394.6,396.6,398.3
XS GIS Cut Line= 4
     1911491.839      400619.907      1911667.79      400730.317
      1911750.52      400784.838      1912063.02      400866.435
#Sta/Elev= 30
       0 1747.34     9.4 1745.37    18.9 1742.43    56.6 1726.78    66.1 1723.39
    75.5 1720.62    94.4 1715.72   113.3 1710.96   122.8 1708.89   132.2 1707.96
   141.6 1707.75   216.7 1708.28   225.7 1707.68   234.7 1705.65   247.7 1701.32
   252.8 1699.83   261.8 1699.91   267.7 1701.47   270.8 1702.29   279.8 1705.52
   288.8 1707.67   316.6 1708.78   375.3 1712.16   414.5 1714.03   522.1 1717.58
   551.5 1719.14   561.3 1720.18   571.1  1721.8   610.2 1729.97   629.8 1733.33
#Mann= 3 , 0 , 0
       0      .1       0   247.7    .045       0   267.7      .1       0
Bank Sta=247.7,267.7
XS Rating Curve= 0 ,0
Exp/Cntr=0.3,0.1

Type RM Length L Ch R = 1 ,10477.6 ,473.4,479.3,485.1
XS GIS Cut Line= 4
     1911260.937      400854.282     1911372.304      400986.914
     1911464.318      401058.094     1911755.728      401177.199
#Sta/Elev= 30
       0  1725.4    19.2 1721.24    28.9 1719.57    38.5 1718.45    57.7 1717.24
    86.6 1715.01   105.8 1713.98   125.1 1713.15   153.9 1711.46   163.6 1710.72
   182.9 1708.76   192.6 1707.23   202.3 1703.99     212 1698.92   220.7 1695.47
   221.7 1695.07   231.4 1694.21   240.7 1695.83   250.7 1698.12   260.4 1699.62
   328.9 1702.23   348.6 1702.49   387.9  1702.4   397.7 1702.64   446.9 1704.93
     506 1708.49   555.1 1710.19     565 1710.78   584.6 1712.41   604.3 1713.56
#Mann= 3 , 0 , 0
       0      .1       0   220.7    .045       0   240.7      .1       0
Bank Sta=220.7,240.7
XS Rating Curve= 0 ,0
Exp/Cntr=0.3,0.1

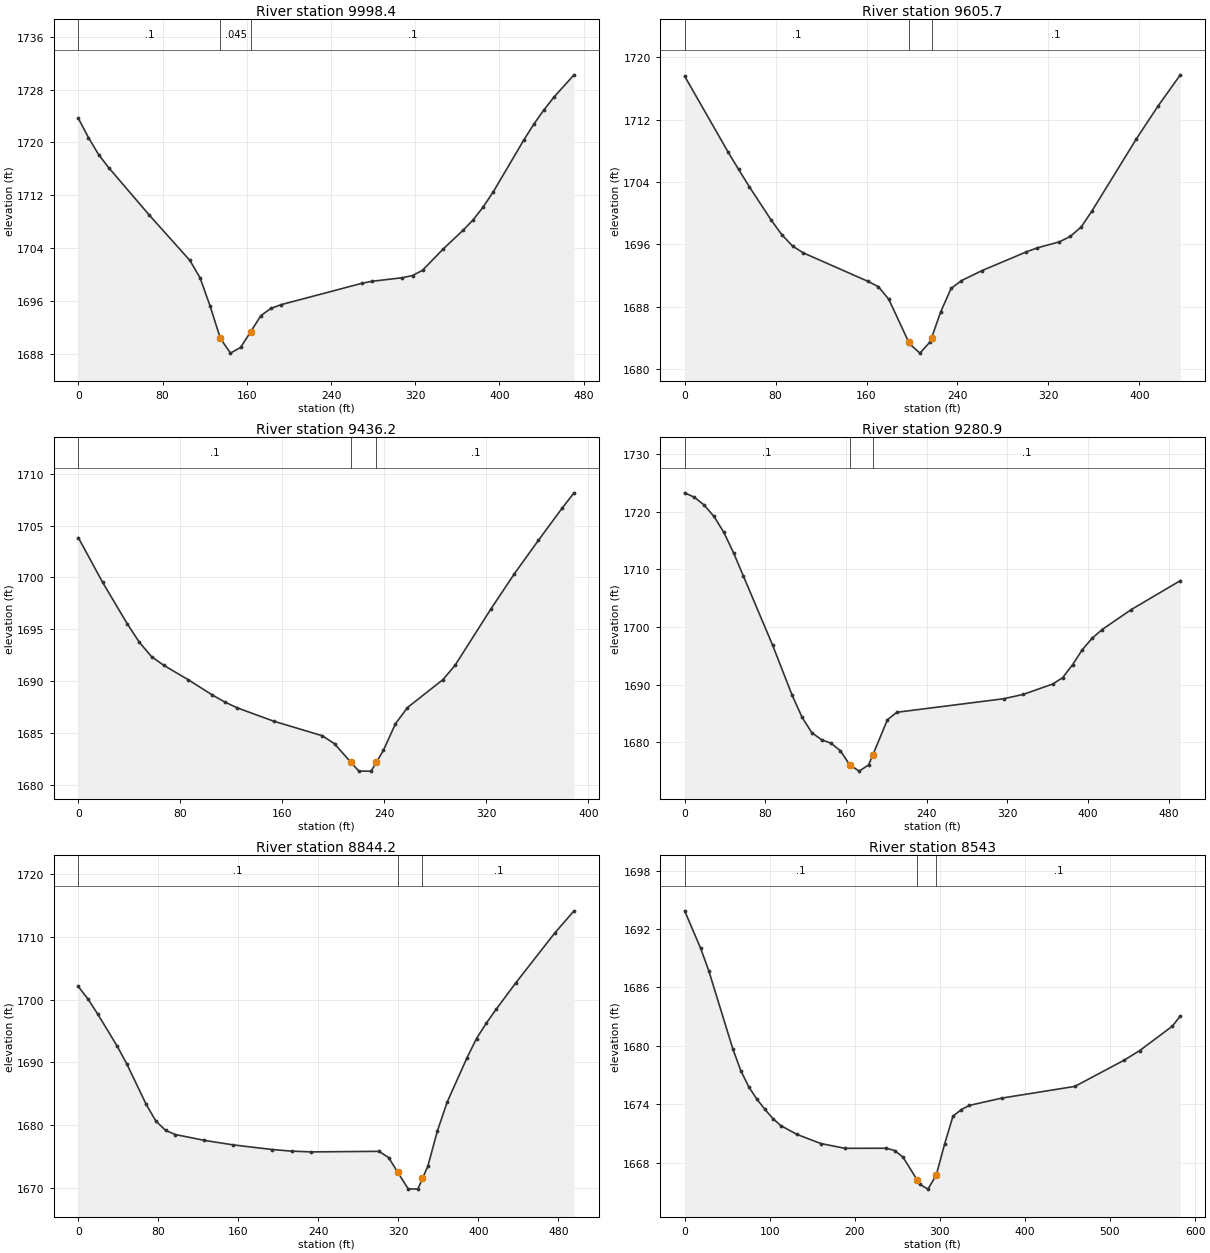
Type RM Length L Ch R = 1 ,9998.4  ,406.6,392.7,378.4
XS GIS Cut Line= 3
      1911038.97      401115.386     1911167.443      401271.636
     1911341.054      401476.497
#Sta/Elev= 30
       0 1723.65     9.6 1720.75    19.3 1718.17    28.9 1716.19    67.4 1709.04
     106 1702.18   115.6 1699.57   125.2 1695.28   134.9 1690.42   144.5 1688.19
   154.1 1689.05   163.8 1691.44   173.4 1693.86     183 1694.95   192.6 1695.51
   269.4 1698.74     279 1699.04   307.8 1699.58   317.4 1699.91     327 1700.71
   346.1 1703.85   365.3 1706.73   374.9  1708.3   384.5 1710.26   394.1 1712.55
   422.9 1720.32   432.4 1722.72     442 1724.88   451.6 1726.83   470.8 1730.22
#Mann= 3 , 0 , 0
       0      .1       0   134.9    .045       0   163.8      .1       0
Bank Sta=134.9,163.8
XS Rating Curve= 0 ,0
Exp/Cntr=0.3,0.1

Type RM Length L Ch R = 1 ,9605.7  ,155.3,169.4,181.9
XS GIS Cut Line= 4
     1910714.318      401424.414     1910847.998      401514.692
     1910943.484      401545.942     1911089.318      401641.428
#Sta/Elev= 29
       0 1717.56      38 1707.89    47.4 1705.62    56.9 1703.39    75.9 1699.16
    85.4 1697.26    94.9 1695.79   104.4 1694.91   161.3 1691.26   170.4 1690.58
   179.6 1688.96   197.2 1683.45   197.8 1683.26     207 1682.06   216.1 1683.53
   217.2 1683.99   225.2 1687.33   234.4 1690.35   243.5 1691.35   261.8 1692.65
   300.5 1695.03   310.2 1695.55   329.6 1696.32   339.2 1697.01   348.9 1698.23
   358.6 1700.34   397.4 1709.52   416.7 1713.78   436.1 1717.73
#Mann= 3 , 0 , 0
       0      .1       0   197.2    .045       0   217.2      .1       0
Bank Sta=197.2,217.2
XS Rating Curve= 0 ,0
Exp/Cntr=0.3,0.1

Type RM Length L Ch R = 1 ,9436.2  ,166.3,155.3,144.7
XS GIS Cut Line= 3
     1910701.996      401512.181      1910860.85      401703.588
     1911000.173      401716.608
#Sta/Elev= 27
       0 1703.84    19.1 1699.52    38.3 1695.55    47.8 1693.76    57.4 1692.37
      67 1691.53    86.1 1690.15   105.2 1688.66   114.8    1688   124.4 1687.44
   153.1 1686.15   191.3 1684.74   200.9 1683.97   213.8 1682.17     220 1681.33
   229.6 1681.33   233.8  1682.2   239.2 1683.33   248.7  1685.9   258.1 1687.46
     286 1690.16   295.4 1691.53   323.4 1696.94     342 1700.37   360.7 1703.57
   379.3 1706.67   388.7 1708.16
#Mann= 3 , 0 , 0
       0      .1       0   213.8    .045       0   233.8      .1       0
Bank Sta=213.8,233.8
XS Rating Curve= 0 ,0
Exp/Cntr=0.3,0.1

Type RM Length L Ch R = 1 ,9280.9  ,443.9,436.7,429.5
XS GIS Cut Line= 4
      1910538.97      401655.317     1910665.707      401703.928
     1910750.776      401742.122     1911012.929      401752.539
#Sta/Elev= 30
       0 1723.26     9.7 1722.49    19.4 1721.13    29.1 1719.16    38.8 1716.43
    48.5 1712.85    58.2 1708.85    87.3 1696.81   106.6 1688.16   116.4 1684.36
     126  1681.7   135.7 1680.46   145.1 1679.86   154.4 1678.55   163.7  1676.1
     173 1675.02   182.4  1676.1   186.6 1677.85     201 1683.92   210.3 1685.22
   316.4 1687.57   335.9 1688.33     365 1690.13   374.7 1691.22   384.5 1693.45
   394.2 1696.07   403.9 1698.04   413.6 1699.53   442.8 1703.03   491.4 1708.04
#Mann= 3 , 0 , 0
       0      .1       0   163.7    .045       0   186.6      .1       0
Bank Sta=163.7,186.6
XS Rating Curve= 0 ,0
Exp/Cntr=0.3,0.1

Type RM Length L Ch R = 1 ,8844.2  ,252.1,301.2,348
XS GIS Cut Line= 3
     1910554.595      401963.476     1910797.651      402123.198
     1911000.776       402149.24
#Sta/Elev= 30
       0  1702.1     9.7 1700.09    19.4  1697.7    38.8 1692.59    48.5 1689.73
    67.9 1683.28    77.6 1680.62    87.2 1679.15      97 1678.48     126 1677.55
   155.1 1676.82   193.9 1676.09   213.3 1675.83   232.7 1675.71   300.6  1675.8
   310.3  1674.8   319.4 1672.44   329.8 1669.82   339.4 1669.77   344.11671.476
   349.4  1673.4   359.1  1679.1   368.8 1683.67   388.4 1690.65   398.1  1693.8
   407.9 1696.25   417.6 1698.43   437.1 1702.62   476.1 1710.58   495.6 1714.17
#Mann= 3 , 0 , 0
       0      .1       0   319.4    .045       0   344.1      .1       0
Bank Sta=319.4,344.1
XS Rating Curve= 0 ,0
Exp/Cntr=0.3,0.1

Type RM Length L Ch R = 1 ,8543    ,279.5,253.6,228.4
XS GIS Cut Line= 4
     1910565.012       402015.56     1910626.605      402203.674
     1910574.522      402319.777     1910767.664      402490.133
#Sta/Elev= 30
       0 1693.86    18.8 1690.01    28.3 1687.72    56.6 1679.69      66 1677.45
    75.4 1675.78    84.8 1674.53    94.3 1673.48   103.7 1672.53   113.1  1671.8
     132  1670.9   160.2 1669.96   188.5 1669.47   237.1 1669.48   246.9 1669.24
   256.7 1668.57   273.6 1666.18   276.2 1665.79     286 1665.28   295.8 1666.73
   305.6 1669.91   315.4 1672.77   325.2 1673.45   334.7 1673.88   372.9 1674.63
   458.7 1675.83     516 1678.49     535 1679.51   573.2 1682.01   582.7 1683.06
#Mann= 3 , 0 , 0
       0      .1       0   273.6    .045       0   295.8      .1       0
Bank Sta=273.6,295.8
XS Rating Curve= 0 ,0
Exp/Cntr=0.3,0.1