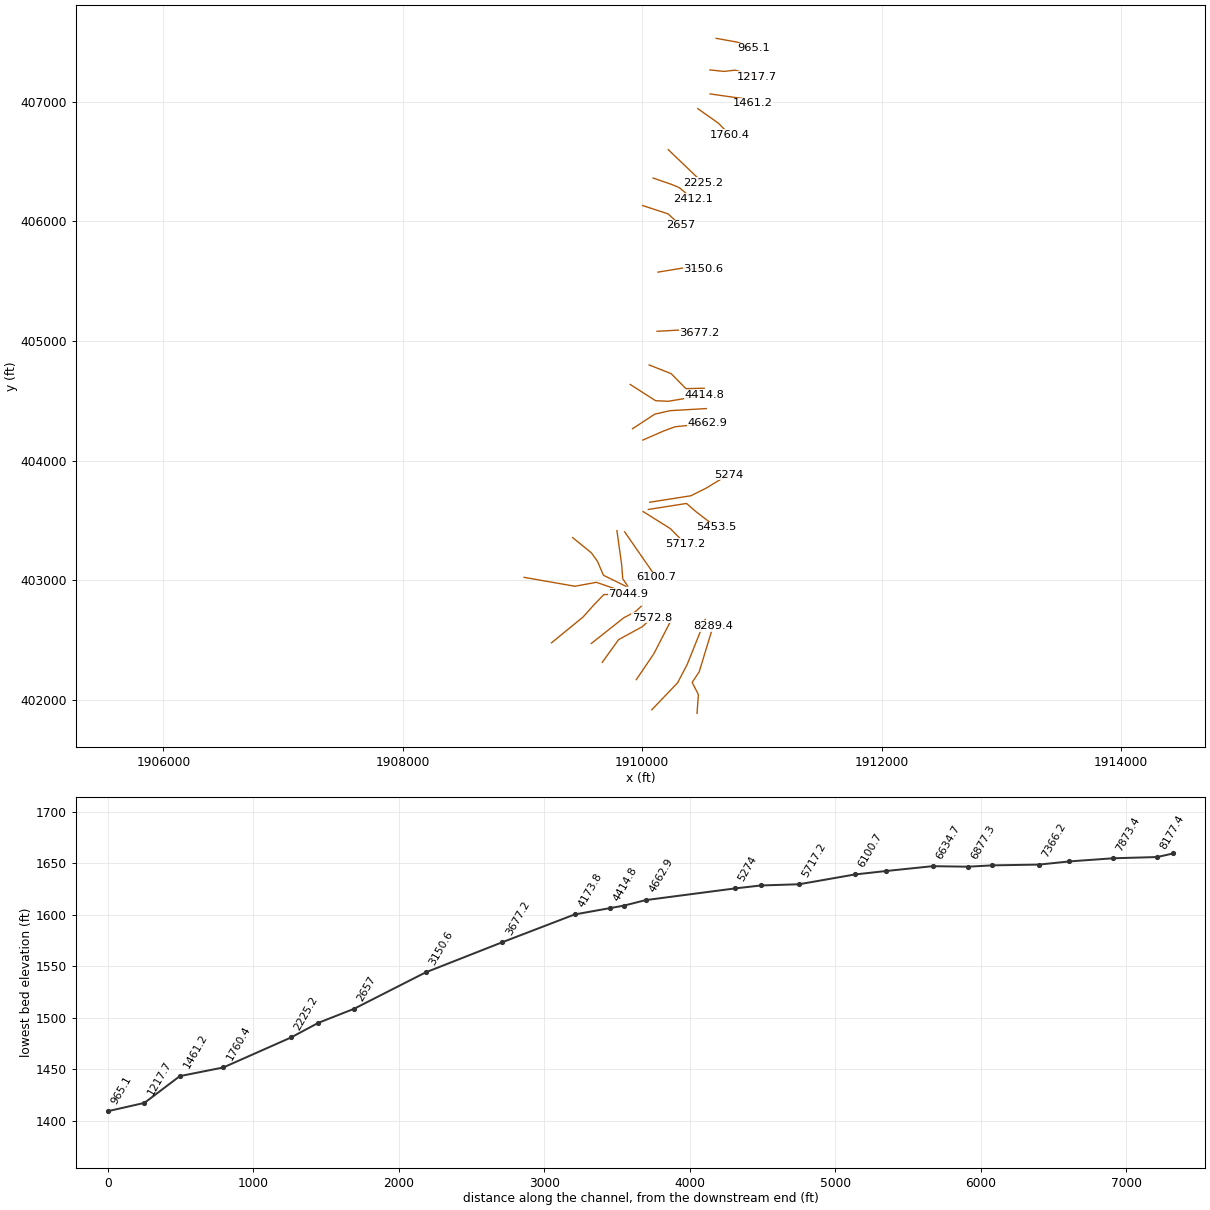
HEC-RAS study SOVERNRN.prj: SOVERNRN

--- SOVERNRN.g01 (geometry) --- (continued)

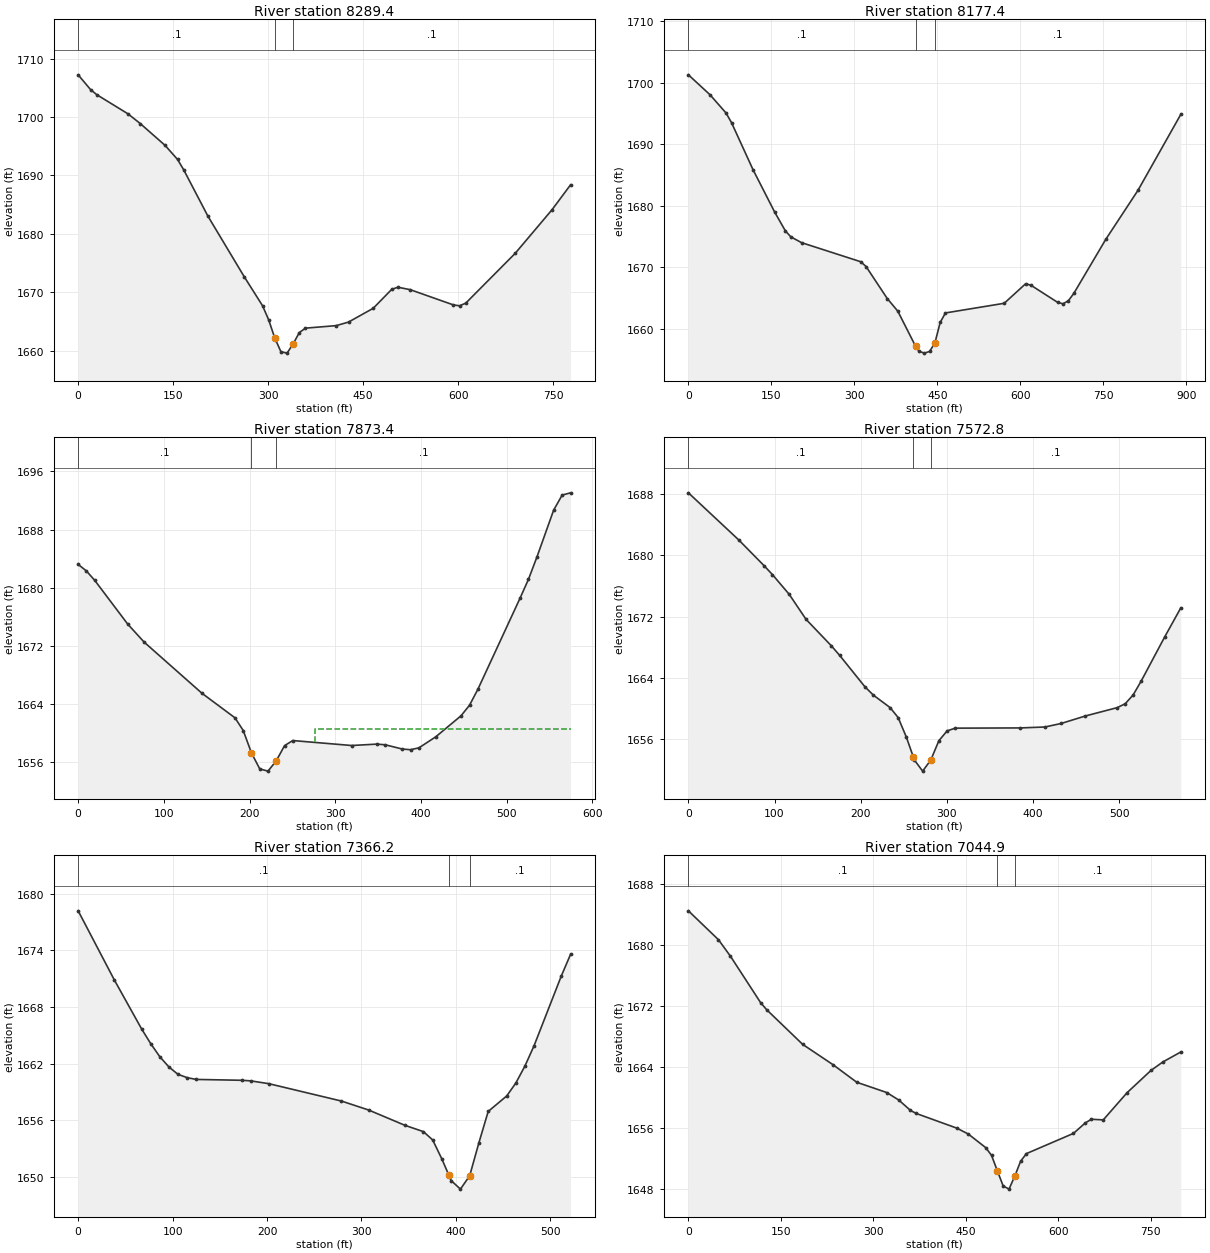
Type RM Length L Ch R = 1 ,8289.4  ,109.2,112,114.9
XS GIS Cut Line= 5
     1910458.159       401888.57     1910469.526      402045.073
     1910417.443      402147.504      1910476.47      402236.046
      1910592.79       402617.99
#Sta/Elev= 30
       0 1707.22    19.6 1704.69    29.4 1703.82    78.5 1700.55    98.1 1698.87
   137.3 1695.13   156.9 1692.73   166.5 1690.98   204.8 1683.03   262.2 1672.64
   291.2 1667.66   300.8 1665.25   310.5 1662.13   320.2 1659.78   329.9 1659.55
   339.6 1661.16   349.2 1663.07   358.9 1663.83   407.5 1664.26   426.9 1664.87
   465.9 1667.23   495.1 1670.47   504.8 1670.84   524.3 1670.42   592.5 1667.81
   602.2 1667.66     612 1668.11   689.9 1676.62   748.3 1684.12   777.5 1688.38
#Mann= 3 , 0 , 0
       0      .1       0   310.5    .045       0   339.6      .1       0
Bank Sta=310.5,339.6
XS Rating Curve= 0 ,0
Exp/Cntr=0.3,0.1

Type RM Length L Ch R = 1 ,8177.4  ,306.8,304.1,301
XS GIS Cut Line= 4
     1910080.555      401918.952     1910295.915      402144.032
     1910375.694      402296.556     1910526.818      402673.546
#Sta/Elev= 30
       0 1701.32    38.9 1698.09    68.1  1695.1    77.9 1693.54   116.8 1685.88
   155.8    1679   175.2 1675.93     185 1674.96   204.4 1674.01   311.5  1670.9
   321.1 1670.12   359.3 1664.92   378.4 1662.86  410.45 1657.16   416.7 1656.34
   426.3 1656.03   435.8  1656.3   445.4 1657.67     455 1661.03   464.5 1662.57
   570.7 1664.14   609.4 1667.32     619 1667.08   667.4 1664.28     677 1664.06
   686.7 1664.56   696.4 1665.74   754.4 1674.57   812.4 1682.52   889.8 1694.88
#Mann= 3 , 0 , 0
       0      .1       0  410.45    .045       0   445.4      .1       0
Bank Sta=410.45,445.4
XS Rating Curve= 0 ,0
Exp/Cntr=0.3,0.1

Type RM Length L Ch R = 1 ,7873.4  ,312.4,300.5,288.4
XS GIS Cut Line= 3
     1909951.258      402170.833     1910097.091      402386.111
     1910241.188      402665.625
#Sta/Elev= 30
       0 1683.21     9.6 1682.31    19.3 1681.02    57.8 1675.01      77 1672.53
   144.5  1665.5     183 1662.13   192.6 1660.39   202.2 1657.31   211.9 1655.11
   221.5 1654.81   231.1 1656.22   240.8 1658.31   250.4 1659.01     319 1658.33
   348.5 1658.52   358.3 1658.43     378 1657.85   387.8 1657.75   397.6 1658.01
   417.3 1659.53   446.7 1662.41   456.6 1663.86   466.4 1666.06   515.5 1678.55
   525.4 1681.16   535.2  1684.2   554.8 1690.67   564.7 1692.73   574.5 1693.04
#Mann= 3 , 0 , 0
       0      .1       0   202.2    .045       0   231.1      .1       0
#XS Ineff= 2 , 0
                          276.44         1660.66
Permanent Ineff=
       F       F
Bank Sta=202.2,231.1
XS Rating Curve= 0 ,0
Exp/Cntr=0.3,0.1

Type RM Length L Ch R = 1 ,7572.8  ,206.6,206.6,206.6
XS GIS Cut Line= 4
     1909666.536       402314.93     1909803.254      402504.817
      1910002.43      402613.397     1910082.725      402689.352
#Sta/Elev= 30
       0 1688.21    58.5 1682.03    87.7 1678.68    97.5  1677.5     117 1674.91
   136.5 1671.64   165.7 1668.19   175.5 1666.92   204.7 1662.82   214.5 1661.72
     234 1660.08   243.4 1658.77   252.9 1656.21   261.2 1653.55   262.3  1653.2
   271.8 1651.75   281.2 1653.19   290.7 1655.74   300.2 1657.02   309.6 1657.38
   385.2 1657.41   413.6 1657.53   432.5 1657.99   460.8 1658.98   497.7 1660.07
   506.9 1660.58   516.1 1661.73   525.3 1663.52   552.9 1669.37   571.4 1673.14
#Mann= 3 , 0 , 0
       0      .1       0   261.2    .045       0   281.2      .1       0
Bank Sta=261.2,281.2
XS Rating Curve= 0 ,0
Exp/Cntr=0.3,0.1

Type RM Length L Ch R = 1 ,7366.2  ,313.2,321.3,329.4
XS GIS Cut Line= 4
     1909574.912      402472.338      1909846.18      402687.181
     1909941.666      402737.095     1909991.579      402782.667
#Sta/Elev= 30
       0 1678.18    38.4 1670.84    67.3 1665.65    76.9  1664.1    86.5 1662.72
    96.1 1661.64   105.7 1660.86   115.4 1660.51     125 1660.32     173 1660.23
   182.6 1660.17   201.9 1659.87   278.8 1658.03   307.6 1657.08     346 1655.46
   365.6 1654.79   375.4 1653.91   385.2 1651.88   392.3 1650.23     395  1649.6
   404.8  1648.7   414.6 1650.12   424.4 1653.63   434.2 1656.93   453.8 1658.57
   463.4 1659.93   473.1 1661.74   482.8  1663.9   511.7  1671.3   521.4 1673.57
#Mann= 3 , 0 , 0
       0      .1       0   392.3    .045       0   414.6      .1       0
Bank Sta=392.3,414.6
XS Rating Curve= 0 ,0
Exp/Cntr=0.3,0.1

Type RM Length L Ch R = 1 ,7044.9  ,183.2,167.6,151.9
XS GIS Cut Line= 5
     1909242.707      402478.125     1909506.965      402694.439
     1909594.526      402792.469     1909679.595      402881.011
      1909882.72      402886.219
#Sta/Elev= 30
       0 1684.43    48.8 1680.64    68.3 1678.47   117.1  1672.4   126.8 1671.48
   185.4 1666.92   234.2 1664.28   273.2 1661.95     322  1660.6   341.5 1659.61
   360.3 1658.26   369.7 1657.86   435.4 1655.94   454.2 1655.16   482.4 1653.38
   491.8 1652.37   501.3 1650.33   510.7 1648.36   520.2 1647.94   529.6 1649.66
   539.1 1651.61   548.5  1652.6   624.8 1655.25   644.1 1656.63   653.8  1657.1
   673.1 1657.02   711.8 1660.59   750.5  1663.5   769.9 1664.62   798.9 1665.92
#Mann= 3 , 0 , 0
       0      .1       0   501.3    .045       0   529.6      .1       0
Bank Sta=501.3,529.6
XS Rating Curve= 0 ,0
Exp/Cntr=0.3,0.1

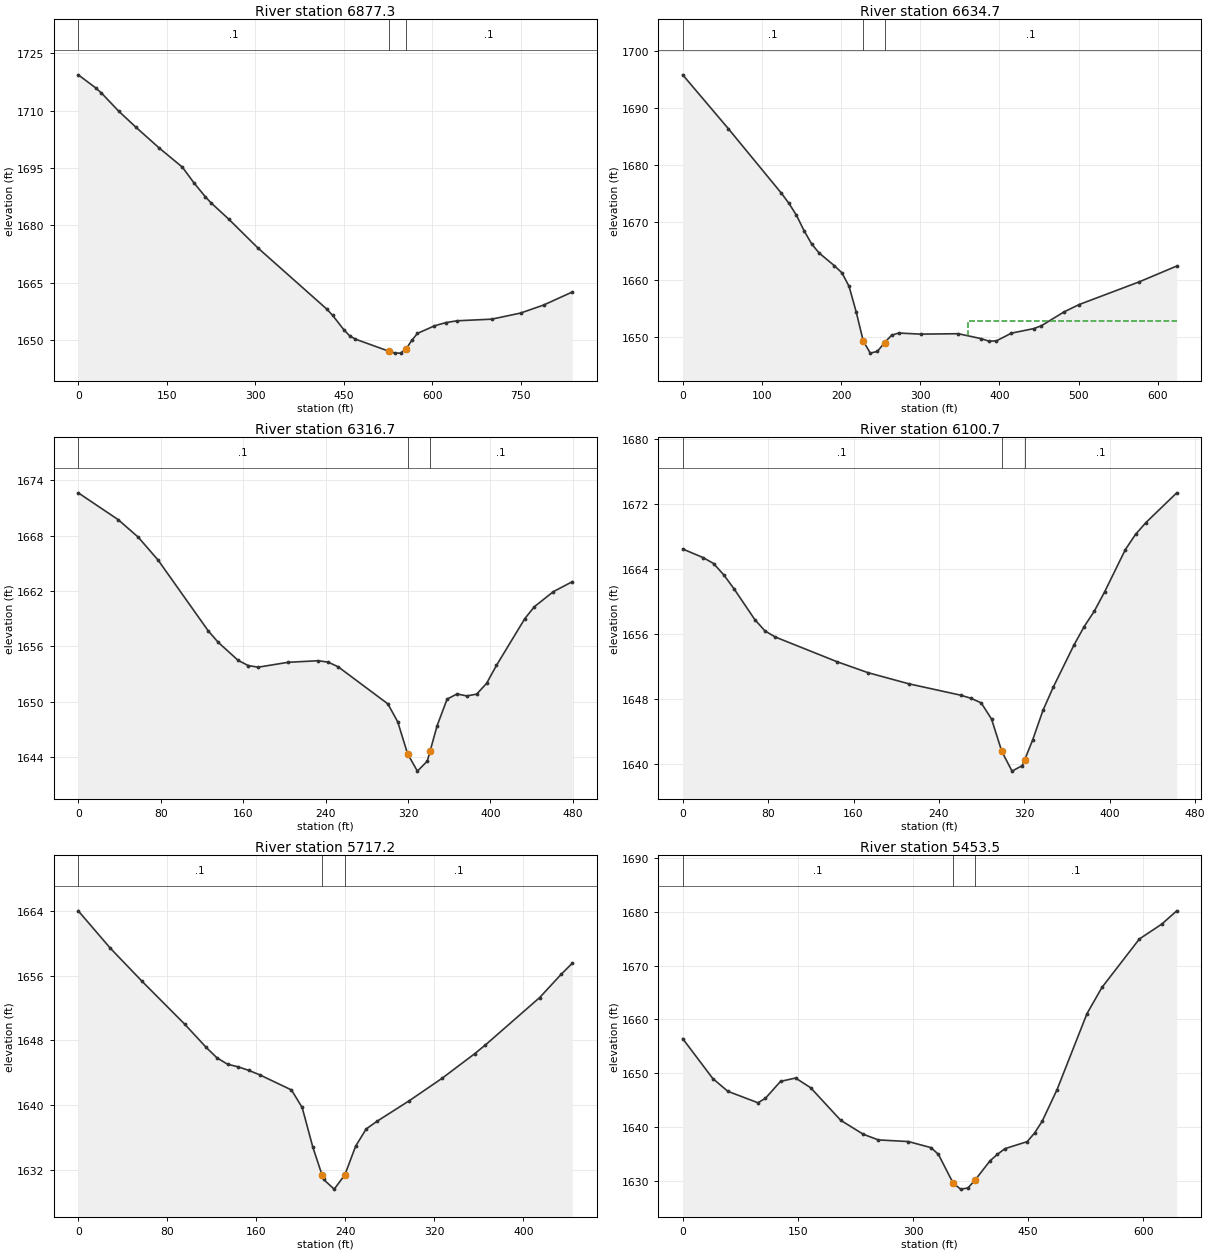
Type RM Length L Ch R = 1 ,6877.3  ,271.1,242.6,214.1
XS GIS Cut Line= 4
     1909013.541         403025.     1909438.276      402950.455
     1909617.095      402983.442     1909828.901      402910.525
#Sta/Elev= 30
       0 1719.33    29.4 1715.94    39.2  1714.6    68.6 1709.84      98 1705.61
   137.2 1700.22   176.4 1695.23     196 1691.13   215.6 1687.44   225.4 1685.85
   254.8 1681.68   303.8 1674.21   421.4 1658.12   431.2 1656.48   450.4 1652.69
   459.9 1651.19   469.5 1650.31   526.9 1647.12   536.5 1646.67   546.1 1646.65
   555.6 1647.75   565.2    1650   574.8  1651.8   603.5 1653.77   622.8 1654.62
   642.3  1655.1   700.7 1655.52   749.4 1657.11   788.4  1659.2   837.1 1662.61
#Mann= 3 , 0 , 0
       0      .1       0   526.9    .045       0   555.6      .1       0
Bank Sta=526.9,555.6
XS Rating Curve= 0 ,0
Exp/Cntr=0.3,0.1

Type RM Length L Ch R = 1 ,6634.7  ,332,317.9,303.8
XS GIS Cut Line= 5
     1909419.179      403356.705     1909575.429      403229.969
     1909627.512      403157.053     1909676.123      403042.469
     1909863.623      402950.455
#Sta/Elev= 30
       0 1695.76    57.5 1686.38   124.5 1675.11   134.1 1673.33   143.7 1671.23
   153.3 1668.53   162.9 1666.22   172.4 1664.63   191.6 1662.42   201.2 1661.17
   210.2 1658.79   219.1 1654.37   228.1 1649.25     237 1647.15     246 1647.46
     255 1648.99   263.9 1650.28   272.9 1650.66   300.4 1650.47   348.2 1650.54
     377 1649.68   386.5 1649.26   396.1 1649.28   415.3 1650.64   443.7 1651.44
   453.2 1651.94   481.7 1654.35   500.7 1655.63   576.7  1659.6   624.1 1662.36
#Mann= 3 , 0 , 0
       0      .1       0   228.1    .045       0     255      .1       0
#XS Ineff= 2 , 0
                          360.38         1652.79
Permanent Ineff=
       F       F
Bank Sta=228.1,255
XS Rating Curve= 0 ,0
Exp/Cntr=0.3,0.1

Type RM Length L Ch R = 1 ,6316.7  ,202.5,216,229.4
XS GIS Cut Line= 4
      1909788.97      403415.733     1909828.901      403127.539
     1909837.582      403012.955     1909879.248      402952.192
#Sta/Elev= 30
       0 1672.64    38.8 1669.73    58.2 1667.84    77.6 1665.34   126.1  1657.7
   135.8 1656.45   155.2 1654.49   164.9 1653.93   174.6 1653.75   203.7 1654.28
   232.8 1654.45   242.5  1654.3   252.2  1653.8   300.5 1649.78   310.1 1647.83
   319.7 1644.36   329.2 1642.49   338.8 1643.58   341.5 1644.66   348.4 1647.43
     358 1650.29   367.6 1650.85   377.1 1650.64   386.7 1650.83   396.3 1651.99
   405.9 1653.94   433.5 1659.02   442.7  1660.3   461.1 1661.93   479.5 1663.01
#Mann= 3 , 0 , 0
       0      .1       0   319.7    .045       0   341.5      .1       0
Bank Sta=319.7,341.5
XS Rating Curve= 0 ,0
Exp/Cntr=0.3,0.1

Type RM Length L Ch R = 1 ,6100.7  ,372.6,383.5,393.5
XS GIS Cut Line= 2
     1909853.207      403405.317     1910117.095      403025.108
#Sta/Elev= 30
       0 1666.48    19.3 1665.41    28.9 1664.69    38.6 1663.27    48.2 1661.55
    67.5 1657.79    77.1 1656.38    86.8 1655.63   144.6 1652.59   173.6 1651.24
   212.1 1649.86   260.3 1648.47     270 1648.09   279.6 1647.52   289.3 1645.53
   298.9 1641.55   308.5 1639.11   318.2  1639.8   320.3 1640.49   327.8 1642.94
   337.5  1646.6   347.1 1649.45   366.4 1654.62     376  1656.9   385.7 1658.85
   395.3 1661.21   414.6 1666.39   424.2 1668.28   433.9 1669.73   462.8  1673.4
#Mann= 3 , 0 , 0
       0      .1       0   298.9    .045       0   320.3      .1       0
Bank Sta=298.9,320.3
XS Rating Curve= 0 ,0
Exp/Cntr=0.3,0.1

Type RM Length L Ch R = 1 ,5717.2  ,263.9,263.7,265.5
XS GIS Cut Line= 3
      1910007.72      403574.587     1910235.151      403432.226
     1910358.415      403307.226
#Sta/Elev= 27
       0 1664.04    28.8 1659.42    57.5  1655.3    95.8    1650     115 1647.14
   124.6 1645.86   134.2 1645.06   143.7 1644.74   153.3  1644.3   162.9 1643.76
   191.6 1641.88   201.2 1639.71   210.8  1634.8     219 1631.39   220.4 1630.81
     230 1629.61   239.6 1631.38   249.2 1634.91   258.7 1637.05   268.3 1637.99
   297.6 1640.56   326.8 1643.31   356.1 1646.35   365.8 1647.44   414.6 1653.31
   434.1 1656.21   443.9 1657.56
#Mann= 3 , 0 , 0
       0      .1       0     219    .045       0   239.6      .1       0
Bank Sta=219,239.6
XS Rating Curve= 0 ,0
Exp/Cntr=0.3,0.1

Type RM Length L Ch R = 1 ,5453.5  ,152.7,179.6,203.1
XS GIS Cut Line= 4
     1910051.123      403591.948     1910370.568      403642.296
     1910450.429      403572.851     1910620.568      403442.643
#Sta/Elev= 30
       0 1656.41    39.2 1648.98    58.8 1646.61      98 1644.48   107.8 1645.32
   127.4 1648.46     147 1649.08   166.6 1647.28   205.8 1641.22   235.2 1638.62
   254.8 1637.57     294 1637.26   323.4 1636.13     333 1634.89   352.2 1629.54
   361.9 1628.41   371.5 1628.62   381.1 1630.15   400.4  1633.7     410 1634.89
   419.6 1635.93   448.7 1637.25   458.4 1638.86   468.2 1641.04   487.6 1646.92
   526.6 1661.07   546.1 1665.94   594.8 1674.95     624 1677.72   643.5 1680.19
#Mann= 3 , 0 , 0
       0      .1       0   352.2    .045       0   381.1      .1       0
Bank Sta=352.2,381.1
XS Rating Curve= 0 ,0
Exp/Cntr=0.3,0.1

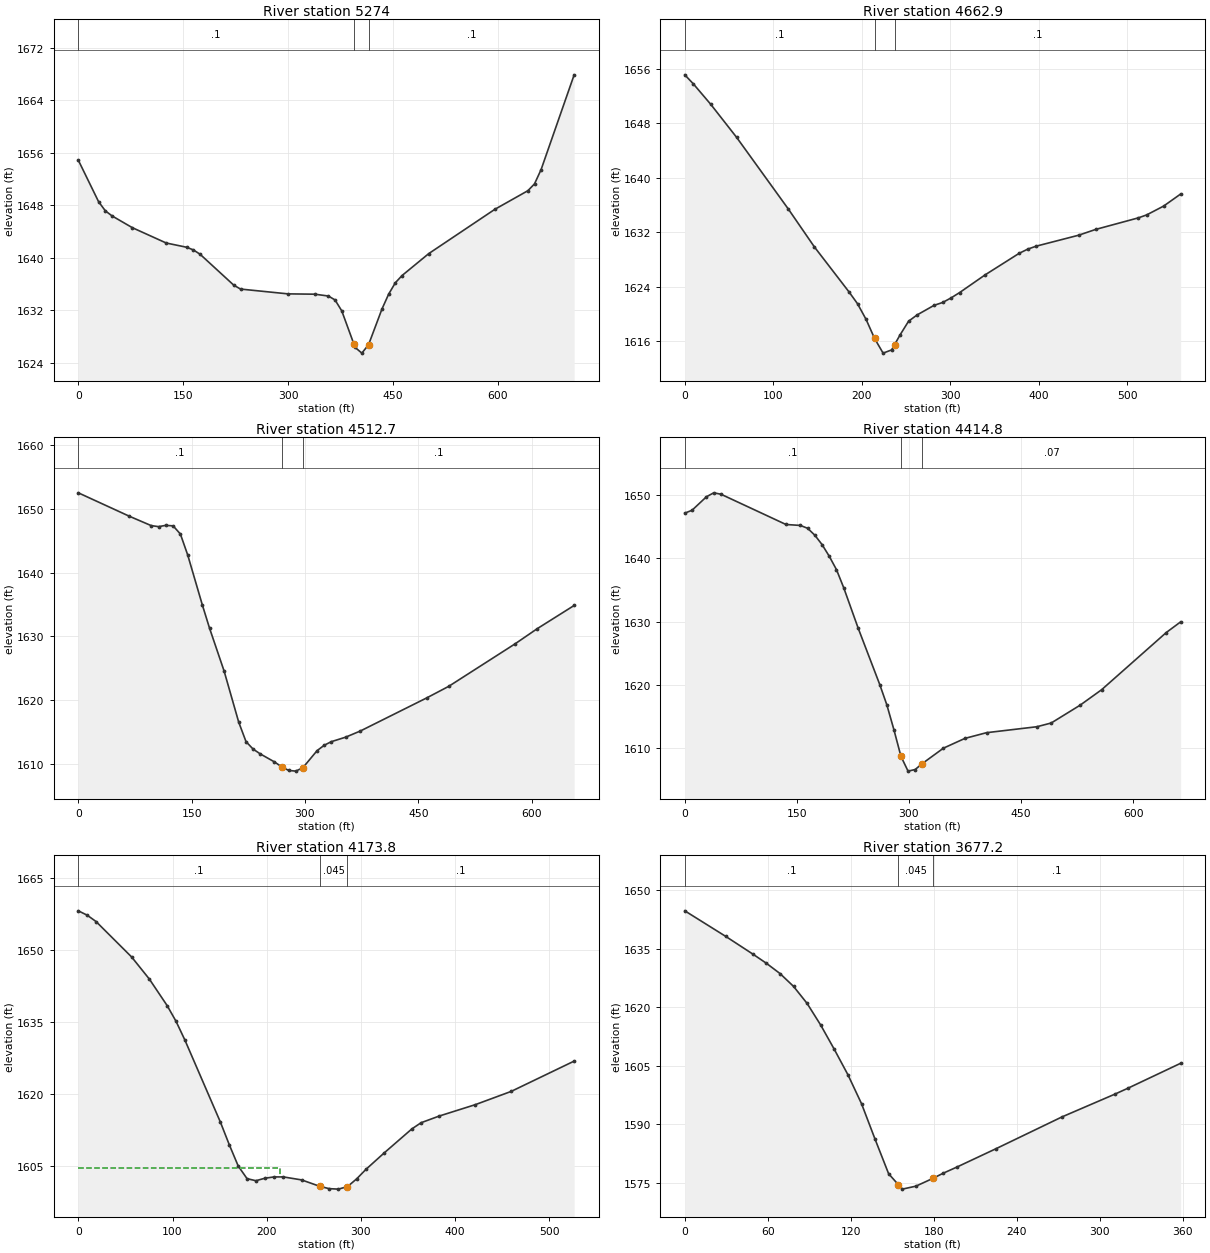
Type RM Length L Ch R = 1 ,5274    ,613.7,611,608.1
XS GIS Cut Line= 4
     1910063.276      403652.365     1910407.026      403706.532
     1910535.498      403770.768     1910721.262      403883.615
#Sta/Elev= 30
       0 1654.87      29 1648.55    38.7 1647.16    48.3 1646.39    77.3  1644.6
   125.7 1642.27   154.7 1641.63   164.3 1641.23     174 1640.57   222.3 1635.85
     232 1635.26   299.7 1634.53   338.3 1634.48   357.6  1634.2   367.1  1633.6
   376.7 1631.94   394.1 1626.87   395.9 1626.37   405.4 1625.51     415 1626.79
   434.2 1632.23   443.8  1634.5   453.3 1636.22   462.9 1637.32   501.1 1640.66
   595.6  1647.4   642.8 1650.23   652.3 1651.27   661.7 1653.44     709 1667.87
#Mann= 3 , 0 , 0
       0      .1       0   394.1    .045       0     415      .1       0
Bank Sta=394.1,415
XS Rating Curve= 0 ,0
Exp/Cntr=0.3,0.1

Type RM Length L Ch R = 1 ,4662.9  ,153.4,150.2,147.1
XS GIS Cut Line= 4
     1910005.984       404171.81     1910184.804      404249.935
     1910275.082      404282.921     1910542.443      404310.698
#Sta/Elev= 30
       0  1655.1     9.8 1653.75    29.3 1650.77    58.5 1645.92   117.1 1635.36
   146.4 1629.82   185.4 1623.23   195.1 1621.48   204.8 1619.17   214.4 1616.37
     224 1614.22   233.6 1614.69   236.9 1615.45   243.2  1616.9   252.8 1618.91
   262.4 1619.83   281.6 1621.24   291.3 1621.66   300.9 1622.34   310.5 1623.12
   339.3 1625.72   377.7 1628.88   387.3 1629.49   396.9 1629.93   444.9 1631.54
   464.1 1632.39   512.1 1634.08   521.7 1634.52   540.9 1635.82   560.1 1637.59
#Mann= 3 , 0 , 0
       0      .1       0   214.4    .045       0   236.9      .1       0
Bank Sta=214.4,236.9
XS Rating Curve= 0 ,0
Exp/Cntr=0.3,0.1

Type RM Length L Ch R = 1 ,4512.7  ,104.7,97.9,90.9
XS GIS Cut Line= 4
     1909919.179      404266.428     1910104.943      404387.955
     1910233.415      404417.469     1910535.498       404434.83
#Sta/Elev= 30
       0 1652.55    67.6 1648.87    96.5  1647.4   106.2 1647.24   115.8 1647.44
   125.5 1647.36   135.1 1646.08   144.8 1642.79   164.1 1634.97   173.7 1631.29
     193 1624.55   212.3 1616.54     222 1613.47   231.4  1612.3   240.8 1611.55
   259.6 1610.29   269.1 1609.52   278.5 1608.95   287.9 1608.84   297.3 1609.38
   316.1 1612.06   325.6 1612.91     335 1613.47   353.8 1614.17   373.3 1615.14
   461.2 1620.34   490.4 1622.16   578.3 1628.84   607.6 1631.22   656.4 1634.86
#Mann= 3 , 0 , 0
       0      .1       0   269.1    .045       0   297.3      .1       0
Bank Sta=269.1,297.3
XS Rating Curve= 0 ,0
Exp/Cntr=0.3,0.1

Type RM Length L Ch R = 1 ,4414.8  ,259.1,240.9,221.5
XS GIS Cut Line= 4
     1909900.082      404636.219     1910111.887      404500.803
     1910216.054      404495.594     1910519.873      404545.942
#Sta/Elev= 30
       0 1647.12     9.7 1647.58      29 1649.71    38.7 1650.33    48.4 1650.11
   135.4 1645.33   154.7 1645.18   164.4 1644.73     174 1643.64   183.7 1642.16
   193.4  1640.3     203  1638.2   212.7 1635.34   232.1 1628.94   260.9 1620.06
   270.4 1616.85   279.8 1612.95   289.3 1608.71   298.8 1606.38   308.3 1606.63
   317.8 1607.57   346.2 1610.01   374.9 1611.55   403.8 1612.45   471.2 1613.39
   490.4 1613.98   528.9 1616.78   557.8 1619.23   644.4 1628.27   663.6 1629.95
#Mann= 3 , 0 , 0
       0      .1       0   289.3    .045       0   317.8     .07       0
Bank Sta=289.3,317.8
XS Rating Curve= 0 ,0
Exp/Cntr=0.3,0.1

Type RM Length L Ch R = 1 ,4173.8  ,475.1,496.6,518.1
XS GIS Cut Line= 4
     1910058.068      404799.414     1910242.095      404726.497
     1910365.359      404601.497     1910518.137      404604.969
#Sta/Elev= 30
       0 1658.22     9.4 1657.31    18.8 1655.99    56.6  1648.6    75.4    1644
    94.3 1638.47   103.7 1635.21   113.1 1631.31   150.8 1614.21   160.2 1609.51
   169.7 1605.07   179.1 1602.43   188.5    1602     198 1602.52   207.7 1602.79
   217.4  1602.8     237 1602.17   256.5 1600.82   266.2 1600.35     276 1600.25
   285.7 1600.77   295.5  1602.4   305.2 1604.35   324.7  1607.8     354 1612.79
   363.8 1614.08     383 1615.47   421.3 1617.84   459.5 1620.61   526.3 1626.92
#Mann= 3 , 0 , 0
       0      .1       0   256.5    .045       0   285.7      .1       0
#XS Ineff= 2 , 0
          213.61 1604.59
Permanent Ineff=
       F       F
Bank Sta=256.5,285.7
XS Rating Curve= 0 ,0
Exp/Cntr=0.3,0.1

Type RM Length L Ch R = 1 ,3677.2  ,523.7,526.6,529
XS GIS Cut Line= 3
      1910124.04      405080.664      1910320.22       405091.08
     1910479.943      405065.039
#Sta/Elev= 24
       0  1644.7    29.5 1638.16    49.1 1633.62    58.9 1631.26    68.8 1628.61
    78.6 1625.31    88.4 1620.94    98.2  1615.4     108 1609.19   117.9 1602.64
   127.7 1595.23   137.5 1586.11   147.3 1577.25  154.421574.416   157.2 1573.31
     167 1574.07   179.3 1576.07   186.6 1577.37   196.5 1578.95     225  1583.7
   272.6 1591.84   310.7 1597.66   320.2 1599.19   358.3 1605.59
#Mann= 3 , 0 , 0
       0      .1       0  154.42    .045       0   179.3      .1       0
Bank Sta=154.42,179.3
XS Rating Curve= 0 ,0
Exp/Cntr=0.3,0.1

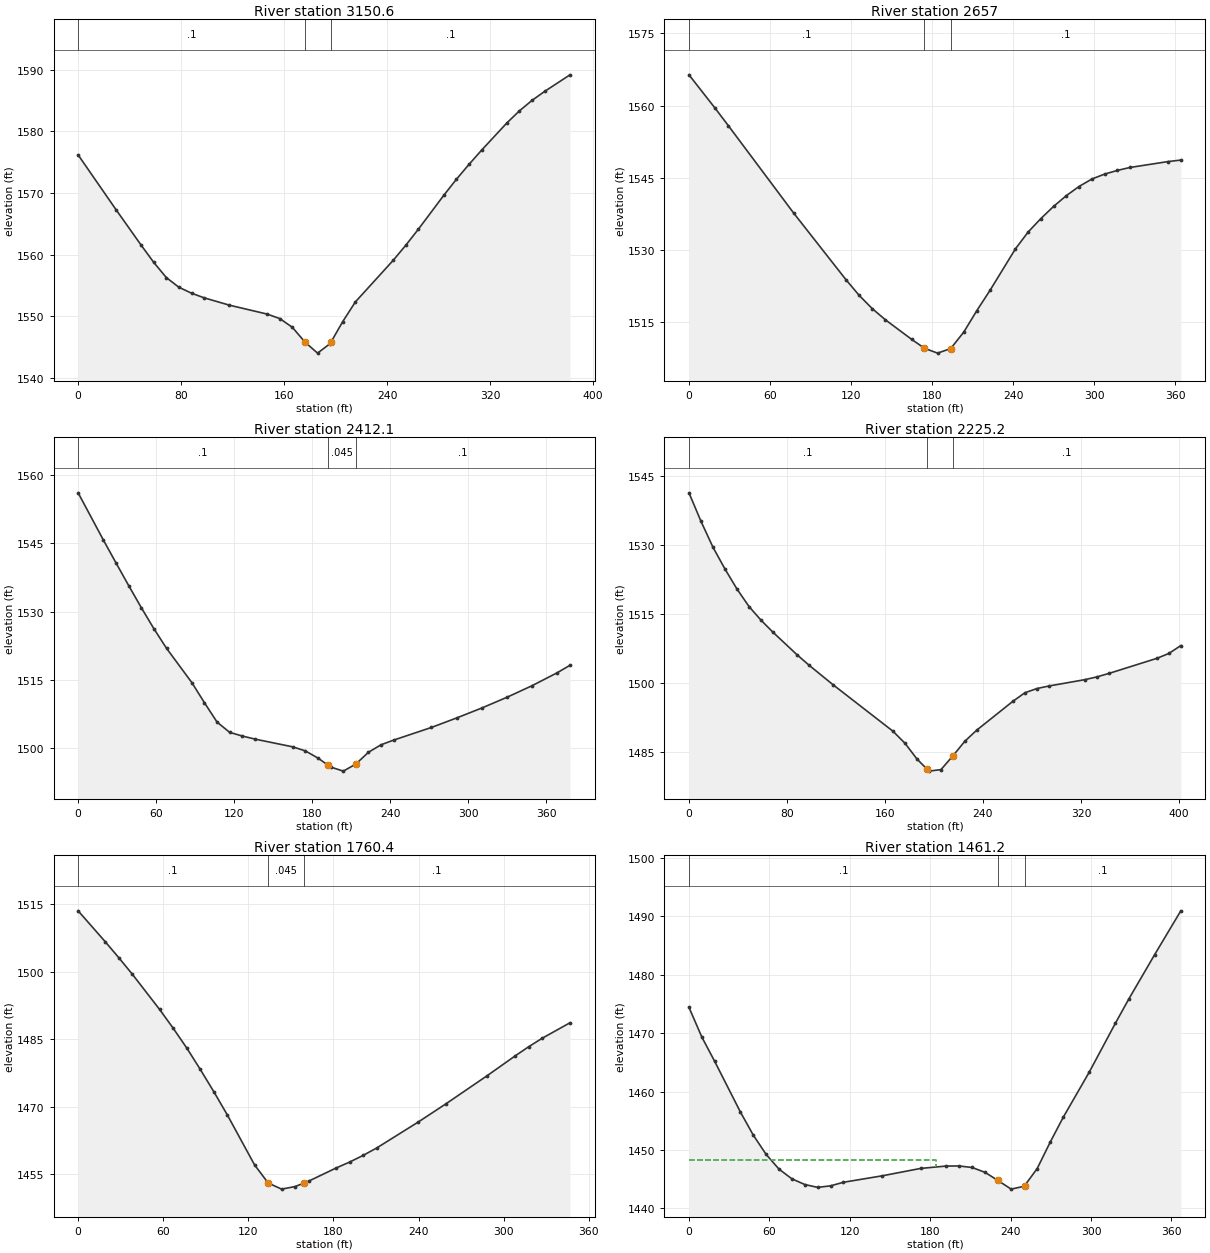
Type RM Length L Ch R = 1 ,3150.6  ,505.5,493.5,481.4
XS GIS Cut Line= 3
     1910131.635      405574.804     1910353.858      405611.263
     1910510.108      405597.374
#Sta/Elev= 30
       0 1576.19    29.4 1567.32      49 1561.54    58.8 1558.74    68.5  1556.3
    78.3 1554.72    88.1 1553.76    97.9 1553.01   117.5 1551.82   146.9 1550.37
   156.7 1549.64   166.4 1548.23   176.2 1545.84     186 1544.04   195.8 1545.59
   196.7 1545.92   205.6 1549.17   215.4 1552.35   244.8  1559.1   254.6 1561.55
   264.4 1564.16     284 1569.62   293.8 1572.22   303.6 1574.64   313.4 1576.95
     333 1581.36   342.8 1583.33   352.6 1585.03   362.4 1586.49   382.1 1589.18
#Mann= 3 , 0 , 0
       0      .1       0   176.2    .045       0   196.7      .1       0
Bank Sta=176.2,196.7
XS Rating Curve= 0 ,0
Exp/Cntr=0.3,0.1

Type RM Length L Ch R = 1 ,2657    ,246.9,244.9,242.8
XS GIS Cut Line= 3
     1910004.248      406131.011     1910216.054      406061.567
      1910320.22       405966.08
#Sta/Elev= 28
       0 1566.38    19.4 1559.43    29.1 1555.84    77.5 1537.68   116.3 1523.82
     126 1520.59   135.7 1517.83   145.4 1515.52   164.8 1511.47   173.8 1509.71
   174.4 1509.59   184.1 1508.59   193.8 1509.54   203.5 1512.97   213.2 1517.44
   222.9 1521.62   241.7 1530.23   251.2 1533.76   260.6 1536.54     270 1539.06
   279.4 1541.29   288.8 1543.19   298.3 1544.74   307.7 1545.76   317.1 1546.52
   326.5 1547.14   354.8 1548.37   364.2 1548.68
#Mann= 3 , 0 , 0
       0      .1       0   173.8    .045       0   193.8      .1       0
Bank Sta=173.8,193.8
XS Rating Curve= 0 ,0
Exp/Cntr=0.3,0.1

Type RM Length L Ch R = 1 ,2412.1  ,195.8,186.9,177.4
XS GIS Cut Line= 4
     1910091.232       406360.72     1910247.482      406306.901
     1910309.982      406280.859     1910421.093      406187.109
#Sta/Elev= 30
       0 1556.09    19.4 1545.74    29.2 1540.67    38.9 1535.72    48.6 1530.88
    58.3 1526.25      68 1521.96    87.5 1514.42    97.2    1510   106.9 1505.75
   116.6  1503.5   126.4 1502.69   136.1 1502.02   165.3 1500.31   174.9 1499.42
   184.6 1497.84   192.5 1496.25   194.3 1495.89     204 1494.99   213.6 1496.53
   223.3 1499.12     233 1500.77   242.7  1501.8   271.7 1504.57   291.1 1506.65
   310.5 1508.84   329.9  1511.2   349.3 1513.76   368.6 1516.59   378.4 1518.23
#Mann= 3 , 0 , 0
       0      .1       0   192.5    .045       0   213.6      .1       0
Bank Sta=192.5,213.6
XS Rating Curve= 0 ,0
Exp/Cntr=0.3,0.1

Type RM Length L Ch R = 1 ,2225.2  ,461,464.9,468.5
XS GIS Cut Line= 2
      1910217.79      406598.025      1910507.72      406320.247
#Sta/Elev= 30
       0 1541.25     9.8 1535.06    19.6 1529.43    29.4  1524.7    39.2 1520.36
      49 1516.57    58.8  1513.6    68.6 1510.98    88.1 1506.12    97.9 1503.85
   117.5 1499.61   166.5  1489.5   176.3 1486.89   186.1 1483.47   193.9 1481.37
   195.9 1480.83   205.7 1481.16   215.4 1484.13   225.2 1487.32     235 1489.75
   264.4 1495.99   274.2 1497.84     284 1498.76   293.8 1499.31   323.2 1500.69
     333 1501.29   342.8 1502.04   381.9 1505.31   391.7 1506.37   401.5 1508.09
#Mann= 3 , 0 , 0
       0      .1       0   193.9    .045       0   215.4      .1       0
Bank Sta=193.9,215.4
XS Rating Curve= 0 ,0
Exp/Cntr=0.3,0.1

Type RM Length L Ch R = 1 ,1760.4  ,286.8,299.1,311.7
XS GIS Cut Line= 3
     1910464.318      406940.907     1910636.193      406819.379
     1910731.679      406722.157
#Sta/Elev= 27
       0 1513.58    19.1 1506.72    28.7 1503.15    38.3 1499.46    57.4 1491.68
      67  1487.5    76.6 1483.09    86.1 1478.35    95.7 1473.37   105.2 1468.22
   124.4 1457.12     134 1453.09   143.5 1451.73   153.1 1452.31   159.4 1453.11
   162.7 1453.53   181.8 1456.41   191.4 1457.74   200.9 1459.22   210.5 1460.87
   239.7 1466.62   259.2 1470.66   288.4 1476.94   307.8 1481.26   317.6 1483.36
   327.3 1485.28   346.8  1488.7
#Mann= 3 , 0 , 0
       0      .1       0     134    .045       0   159.4      .1       0
Bank Sta=134,159.4
XS Rating Curve= 0 ,0
Exp/Cntr=0.3,0.1

Type RM Length L Ch R = 1 ,1461.2  ,237,243.6,249.4
XS GIS Cut Line= 4
     1910567.327      407063.469      1910766.98      407035.257
     1910834.254      407026.577     1910922.145      406984.259
#Sta/Elev= 30
       0 1474.41     9.6 1469.32    19.2 1465.16    38.4 1456.49      48 1452.54
    57.6 1449.24    67.2 1446.73    76.8 1445.07    86.4  1444.1      96 1443.61
   105.6 1443.87   115.2 1444.48     144 1445.58   172.8 1446.85     192 1447.26
   201.6 1447.27   211.3 1447.01     221 1446.17   230.5 1444.79   240.4 1443.31
   250.1  1443.8   250.5 1443.92   259.8 1446.82   269.5 1451.33   279.2 1455.58
   298.7 1463.34   318.2  1471.7     328 1475.76   347.5 1483.44     367 1490.92
#Mann= 3 , 0 , 0
       0      .1       0   230.5    .045       0   250.5      .1       0
#XS Ineff= 2 , 0
          184.41 1448.26
Permanent Ineff=
       F       F
Bank Sta=230.5,250.5
XS Rating Curve= 0 ,0
Exp/Cntr=0.3,0.1

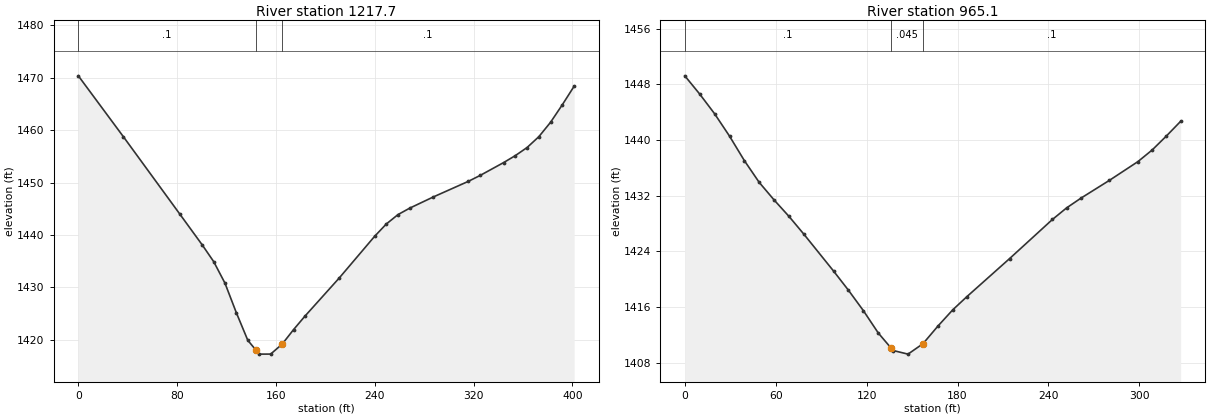
Type RM Length L Ch R = 1 ,1217.7  ,260,252.5,245.4
XS GIS Cut Line= 4
     1910566.748      407263.823     1910684.804      407251.671
     1910776.818      407262.087     1910959.109      407208.268
#Sta/Elev= 29
       0 1470.33    36.5 1458.72    82.2 1443.97   100.4 1438.08   109.6 1434.92
   118.7 1430.83   127.9  1425.2   137.2 1419.93   143.5 1418.15   146.5  1417.3
   155.7 1417.31     165  1419.2   174.2 1421.96   183.5 1424.55   211.3 1431.83
   239.8 1439.73   249.3 1442.09   258.8 1443.89   268.3 1445.12   287.3 1447.24
   315.8 1450.23   325.3 1451.35   344.3  1453.8   353.8 1455.13   363.3 1456.67
   372.8 1458.73   382.3 1461.48   391.8 1464.81   401.4 1468.36
#Mann= 3 , 0 , 0
       0      .1       0   143.5    .045       0     165      .1       0
Bank Sta=143.5,165
XS Rating Curve= 0 ,0
Exp/Cntr=0.3,0.1

Type RM Length L Ch R = 1 ,965.1   ,266.1,269.8,272.5
XS GIS Cut Line= 3
     1910617.783      407527.879      1910791.81      407496.629
     1910932.887      407444.545
#Sta/Elev= 29
       0 1449.21     9.8  1446.6    19.6 1443.78    29.5 1440.55    39.3 1437.03
    49.1  1433.9    58.9 1431.38    68.8    1429    78.6 1426.45    98.2 1421.15
     108  1418.4   117.9 1415.45   127.7 1412.25   135.9 1410.15   137.5 1409.74
   147.3 1409.22   157.2 1410.72     167 1413.24   176.8 1415.58   186.2 1417.49
   214.4 1422.96   242.6 1428.57     252 1430.24   261.4 1431.63   280.2 1434.19
     299 1436.88   308.4 1438.55   317.8 1440.56   327.2 1442.67
#Mann= 3 , 0 , 0
       0      .1       0   135.9    .045       0   157.2      .1       0
Bank Sta=135.9,157.2
XS Rating Curve= 0 ,0
Exp/Cntr=0.3,0.1