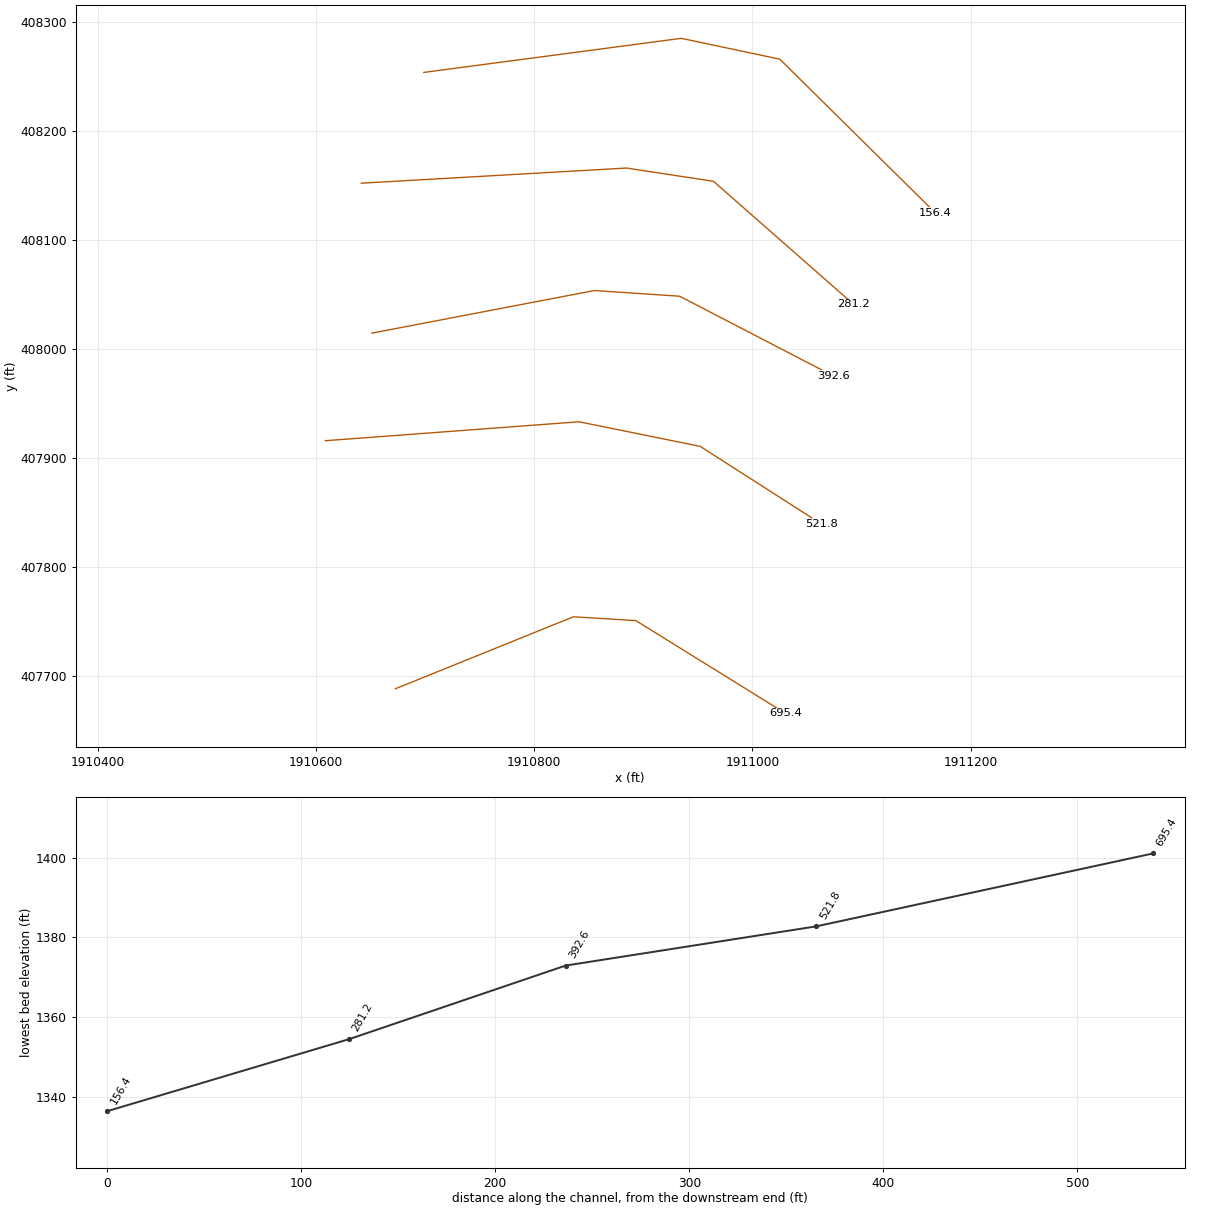
HEC-RAS study SOVERNRN.prj: SOVERNRN

--- SOVERNRN.g01 (geometry) --- (continued)

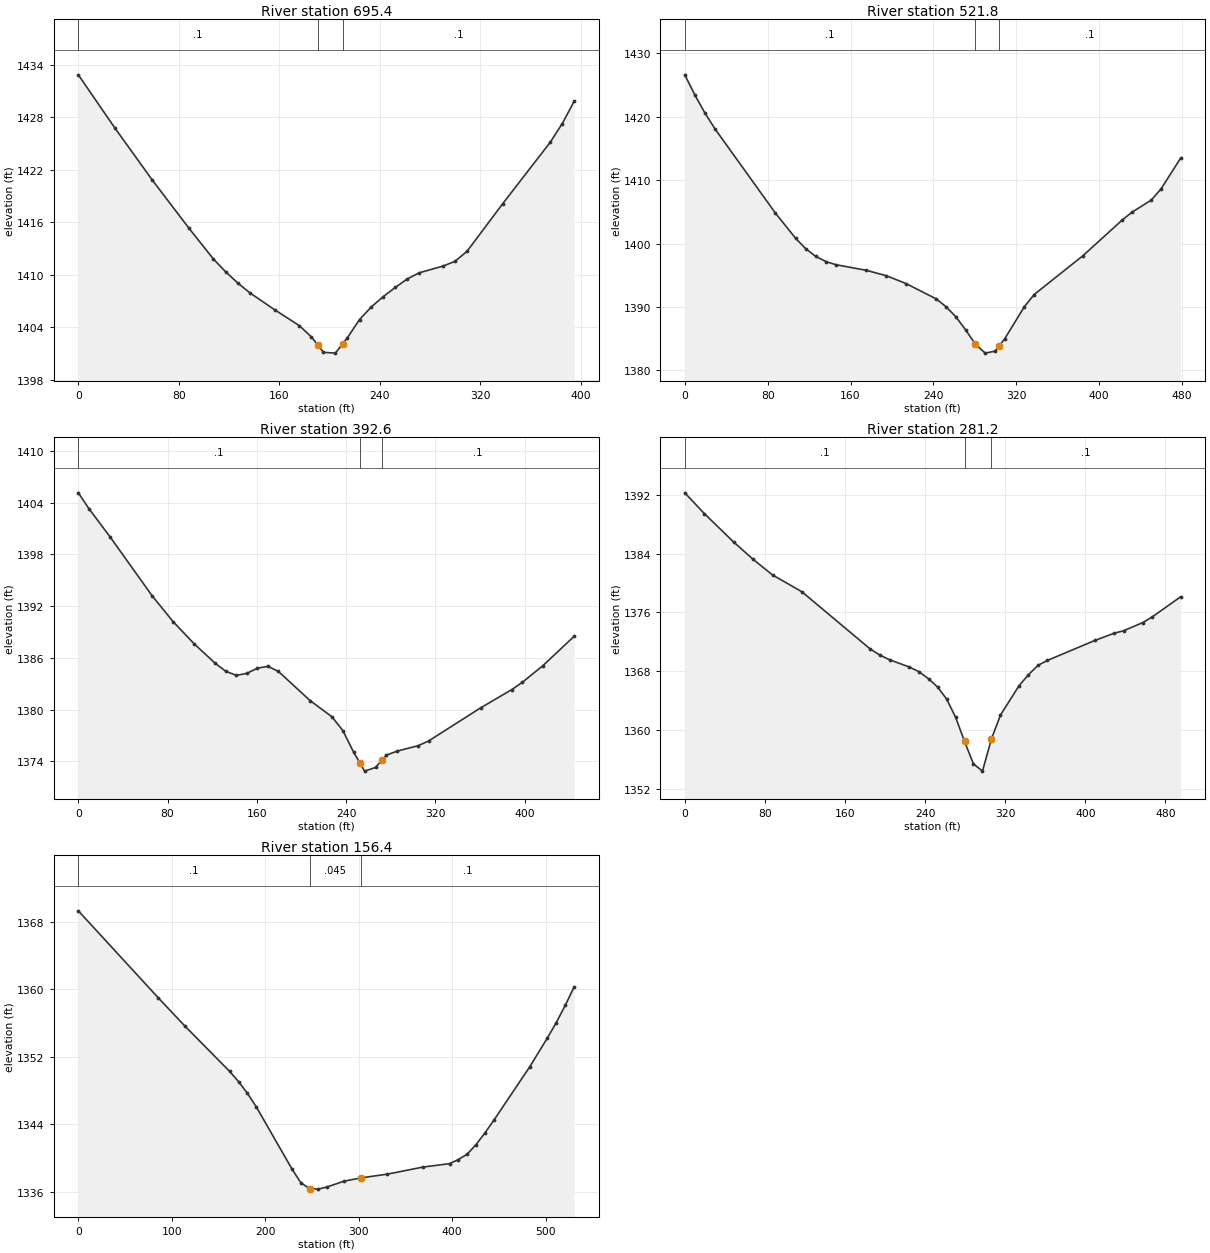
Type RM Length L Ch R = 1 ,695.4   ,177.5,173.6,170
XS GIS Cut Line= 4
     1910672.651      407688.303     1910835.845      407754.275
     1910893.137      407750.803      1911030.29      407665.733
#Sta/Elev= 29
       0 1432.85    29.3 1426.73    58.7 1420.86      88 1415.33   107.6 1411.79
   117.4 1410.32   127.1 1409.03   136.9  1407.9   156.5 1405.98     176 1404.18
   185.6 1402.89   190.5 1401.99   195.2 1401.13   204.7 1401.04   210.5 1402.11
   214.3 1402.81   223.9 1404.88   233.4 1406.34   242.9 1407.51   252.4 1408.55
   261.9 1409.52   271.4 1410.22   290.4 1410.99   299.9 1411.53   309.4 1412.66
   337.8  1418.1   375.8 1425.15   385.3 1427.27   394.8 1429.83
#Mann= 3 , 0 , 0
       0      .1       0   190.5    .045       0   210.5      .1       0
Bank Sta=190.5,210.5
XS Rating Curve= 0 ,0
Exp/Cntr=0.3,0.1

Type RM Length L Ch R = 1 ,521.8   ,125.7,129.2,131.3
XS GIS Cut Line= 4
     1910608.415      407915.733     1910841.054      407933.094
     1910952.165      407910.525     1911063.276      407839.344
#Sta/Elev= 30
       0 1426.63     9.7 1423.46    19.4 1420.62    29.2 1418.09    87.5 1404.81
   106.9 1400.86   116.6 1399.22   126.4 1397.99   136.1 1397.18   145.8 1396.68
     175  1395.8   194.4 1394.95   213.8 1393.69   242.7 1391.28   252.2 1390.05
   261.6 1388.47   271.1 1386.39   280.5 1384.14     290 1382.73   299.4 1383.04
   303.2 1383.83   308.9 1385.02   327.8 1390.06   337.2 1391.97   384.4 1398.11
   422.1 1403.71   431.5 1404.94   450.4 1406.89   459.8 1408.66   478.6 1413.49
#Mann= 3 , 0 , 0
       0      .1       0   280.5    .045       0   303.2      .1       0
Bank Sta=280.5,303.2
XS Rating Curve= 0 ,0
Exp/Cntr=0.3,0.1

Type RM Length L Ch R = 1 ,392.6   ,113.5,111.5,110.5
XS GIS Cut Line= 4
     1910651.128      408014.366     1910855.121      408053.428
     1910933.246       408048.22     1911073.871      407975.303
#Sta/Elev= 30
       0 1405.14     9.4 1403.32    28.3 1400.06    66.1 1393.21      85  1390.2
   103.8 1387.64   122.7 1385.38   132.2 1384.45   141.6 1383.98     151 1384.21
   160.5 1384.81   169.9 1385.03   179.4 1384.43   207.7 1381.06   227.3 1379.18
   237.1 1377.58   246.8 1375.06   252.2 1373.86   256.6 1372.88   266.4 1373.31
   272.2 1374.16   276.2 1374.74     286 1375.21   304.6 1375.83     314 1376.38
   360.5 1380.21   388.5 1382.33   397.8 1383.16   416.4 1385.11   444.4 1388.51
#Mann= 3 , 0 , 0
       0      .1       0   252.2    .045       0   272.2      .1       0
Bank Sta=252.2,272.2
XS Rating Curve= 0 ,0
Exp/Cntr=0.3,0.1

Type RM Length L Ch R = 1 ,281.2   ,126.3,124.8,123.3
XS GIS Cut Line= 4
     1910641.401      408151.844     1910884.457      408165.733
     1910964.318       408153.58      1911092.79      408040.733
#Sta/Elev= 30
       0 1392.27    19.5 1389.45    48.7 1385.59    68.2 1383.23    87.6  1381.1
   116.9 1378.82     185 1371.05   194.8  1370.2   204.5 1369.57     224 1368.59
   233.7 1367.96   243.4 1366.99   252.4 1365.87   261.4 1364.24   270.4 1361.77
   279.4 1358.45   288.3  1355.4   297.3 1354.42   306.3 1358.82   315.3 1362.05
   333.7 1366.01   343.2 1367.53   352.7  1368.8   362.2 1369.48   409.7  1372.2
   428.7 1373.17   438.2 1373.51   457.2 1374.61   466.7 1375.38   495.2 1378.13
#Mann= 3 , 0 , 0
       0      .1       0   279.4    .045       0   306.3      .1       0
Bank Sta=279.4,306.3
XS Rating Curve= 0 ,0
Exp/Cntr=0.3,0.1

Type RM Length L Ch R = 1 ,156.4   ,162.4,156.4,150.3
XS GIS Cut Line= 4
     1910698.693      408253.407     1910934.804      408284.657
     1911025.082       408265.56     1911167.443      408124.935
#Sta/Elev= 27
       0  1369.3    85.7 1358.97   114.3 1355.61     162 1350.26   171.5 1349.05
     181 1347.66   190.5 1346.05   228.6  1338.7   238.2 1337.05   247.4 1336.38
   256.6 1336.31   265.6 1336.55   284.3 1337.25   302.8 1337.65   330.4 1338.08
   368.6 1338.92   397.2 1339.33   406.7 1339.82   416.2 1340.46   425.7  1341.6
   435.3    1343   444.8  1344.5   482.9 1350.78     502 1354.24   511.5 1356.06
     521 1358.08   530.6 1360.28
#Mann= 3 , 0 , 0
       0      .1       0   247.4    .045       0   302.8      .1       0
Bank Sta=247.4,302.8
XS Rating Curve= 0 ,0
Exp/Cntr=0.3,0.1

Chan Stop Cuts=-1
Use User Specified Reach Order=0
Composite Channel Slope=5